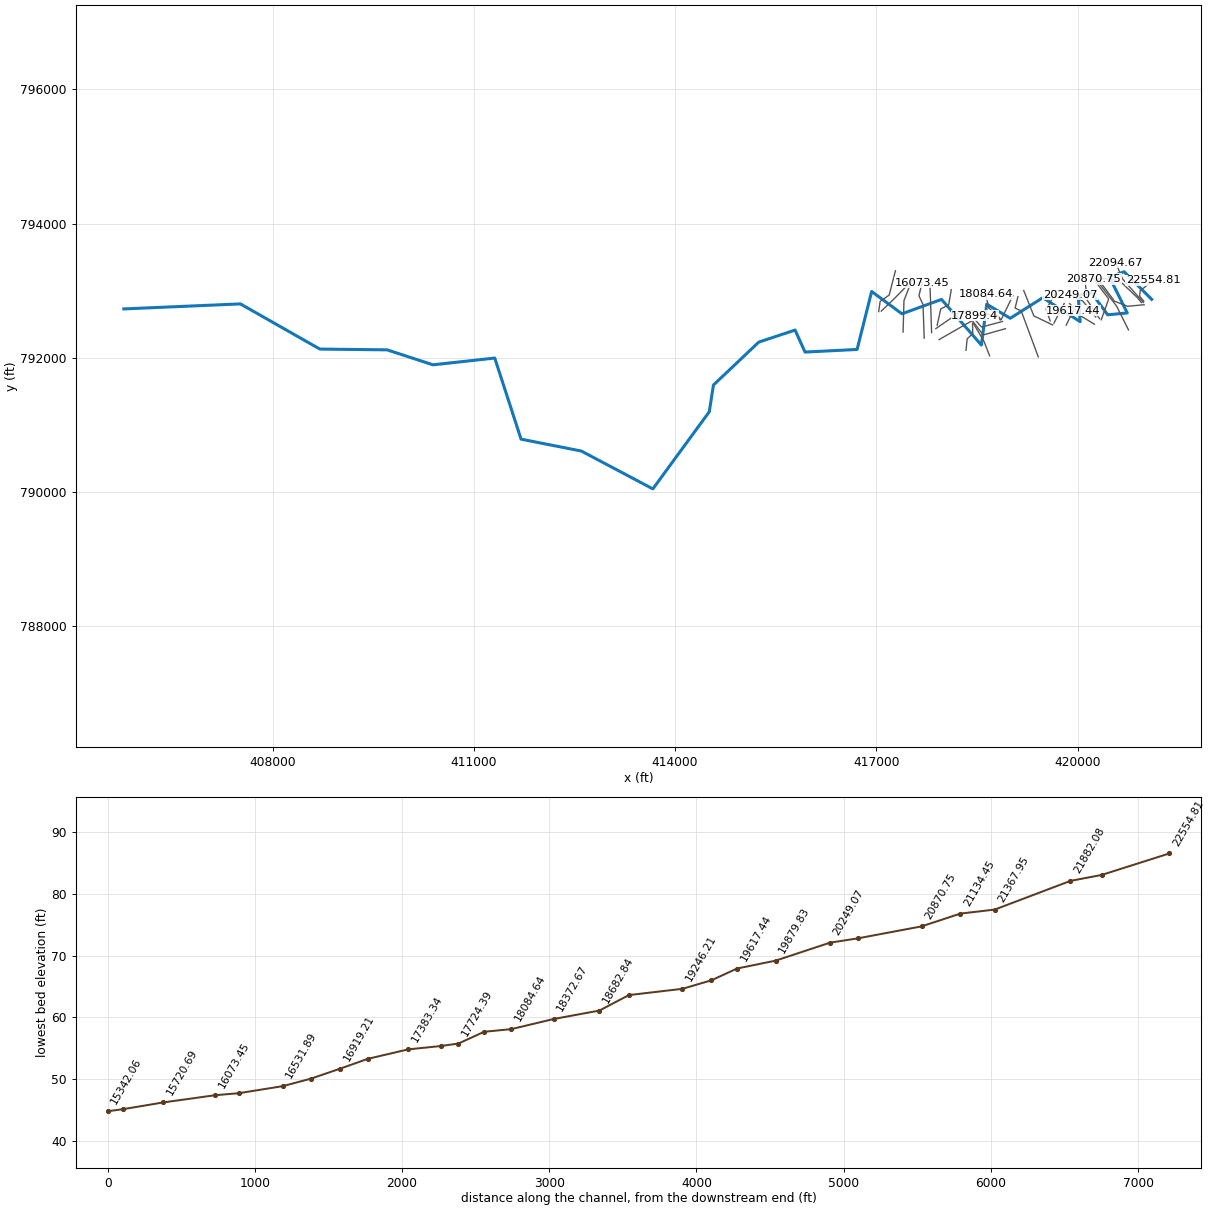
--- 4217_ras.prj (project) ---

Proj Title=4217
Current Plan=p01
Default Exp/Contr=0.3,0.1
English Units
Geom File=g01
Flow File=f01
Plan File=p01
Y Axis Title=Elevation
X Axis Title(PF)=Main Channel Distance
X Axis Title(XS)=Station
BEGIN DESCRIPTION:
RFD model 4217 exported to HEC-RAS
END DESCRIPTION:

--- 4217_ras.p01 (plan) ---

Plan Title=Plan 01
Program Version=4.10
Short Identifier=Plan 01
Geom File=g01
Flow File=f01
Subcritical Flow
Calc Critical at every XS
Secant Critical Depth

--- 4217_ras.f01 (steady flow) ---

Flow Title=Flow 01
Program Version=5.01
Number of Profiles= 6
Profile Names=10yr,25yr,50yr,100yr,100plus,500yr
River Rch & RM=4217,69,22554.81
 4783.58 7616.4810279.3112643.6818459.7819719.82
River Rch & RM=4217,69,22094.67
 4798.24 7640.84 10313.112686.2218521.8819780.11
River Rch & RM=4217,69,21882.08
 4800.35 7644.3310317.9412692.3118530.7819788.72
River Rch & RM=4217,69,21367.95
 4809.68 7659.9210339.6412719.7118570.7819827.82
River Rch & RM=4217,69,21134.45
 4811.38 7662.7610343.5812724.6718578.0219834.86
River Rch & RM=4217,69,20870.75
 4813.28 7665.9110347.9612730.1818586.0719842.67
River Rch & RM=4217,69,20436.19
 4829.79 7693.2510385.8212777.7918655.5719909.84
River Rch & RM=4217,69,20249.07
 4832.64 7697.9910392.3912786.0618667.6419921.55
River Rch & RM=4217,69,19879.83
 4834.16 7700.51 10395.912790.4618674.0819927.79
River Rch & RM=4217,69,19617.44
  4847.6 7722.8610426.9212829.5418731.1319983.16
River Rch & RM=4217,69,19443.89
 4848.36 7724.1210428.6712831.7418734.3519986.28
River Rch & RM=4217,69,19246.21
 4851.01 7728.5310434.7912839.4618745.6119997.19
River Rch & RM=4217,69, 18882.4
 5961.01 9516.8712869.2715852.3123144.3724018.45
River Rch & RM=4217,69,18682.84
 5962.11 9518.6912871.7915855.4923149.01 24022.8
River Rch & RM=4217,69,18372.67
 5972.33 9535.6612895.33 15885.123192.2424063.39
River Rch & RM=4217,69,18084.64
 5973.99  9538.412899.1315889.8723199.2124069.91
River Rch & RM=4217,69, 17899.4
 5976.75 9542.9712905.4615897.8323210.8324080.78
River Rch & RM=4217,69,17724.39
 5977.49 9544.1912907.1515899.9523213.9224083.67
River Rch & RM=4217,69,17605.23
 5978.22 9545.4112908.8415902.0723217.0224086.57
River Rch & RM=4217,69,17383.34
 5978.41 9545.7112909.26 15902.6 23217.8 24087.3
River Rch & RM=4217,69,17108.66
 6118.04 9778.1213232.1916309.5823811.9924646.07
River Rch & RM=4217,69,16919.21
 6119.14 9779.9413234.7116312.7523816.6124650.37
River Rch & RM=4217,69,16722.99
 6122.25  9785.113241.8516321.7223829.7124662.57
River Rch & RM=4217,69,16531.89
 6127.56 9793.8913254.0316337.0123852.0424683.38
River Rch & RM=4217,69,16233.78
 6135.63 9807.2413272.5116360.2323885.9324714.94
River Rch & RM=4217,69,16073.45
 6141.35 9816.6813285.5616376.6223909.8624737.16
River Rch & RM=4217,69,15720.69
  6147.8 9827.33 13300.316395.1123936.8624762.24
River Rch & RM=4217,69,15445.58
 6149.83 9830.6813304.9316400.9323945.3524770.12
River Rch & RM=4217,69,15342.06
 6150.93 9832.5113307.46 16404.123949.9824774.42
River Rch & RM=4217,69,15112.45
 6270.1110028.9313578.7416744.1624446.4825233.34
River Rch & RM=4217,69, 14806.8
 6273.7910034.9913587.1316754.6924461.8525247.56
River Rch & RM=4217,69,14658.76
 6275.6210038.0213591.3216759.9524469.5325254.67
River Rch & RM=4217,69,14437.74
 6282.4210049.2413606.8316779.4224497.9525280.97
River Rch & RM=4217,69,13996.98
 7920.6712696.4817218.43 21256.1 31033.931040.48
River Rch & RM=4217,69,13618.37
 7928.0312708.6317235.2321277.1831064.6931068.01
River Rch & RM=4217,69,13294.97
  7930.312712.3817240.4221283.7131074.2131076.53
River Rch & RM=4217,69,12902.89
 7935.7112721.32 17252.821299.2531096.9131096.84
River Rch & RM=4217,69,12632.27
 8013.9112850.3817431.2521523.0931423.71 31388.5
River Rch & RM=4217,69,12469.58
 8015.1312852.3917434.0421526.5931428.8231393.06
River Rch & RM=4217,69,12334.46
 8016.1812854.1217436.43 21529.631433.2131396.98
River Rch & RM=4217,69,12086.19
  8029.6 12876.317467.1321568.1331489.4731447.22
River Rch & RM=4217,69,11837.91
 8035.0212885.2517479.5121583.6531512.1431467.44
River Rch & RM=4217,69,11589.64
 8040.7912894.7717492.6721600.1731536.2531488.96
River Rch & RM=4217,69,11244.64
 8055.9212919.7817527.2921643.6531599.7331545.65
River Rch & RM=4217,69,10717.35
 8079.8312959.2717581.9121712.1831699.7931634.85
River Rch & RM=4217,69,9790.033
 8090.63 12977.117606.5921743.1631745.0131675.19
River Rch & RM=4217,69, 9058.36
 8375.21 13446.318255.0222556.1332931.9532727.88
River Rch & RM=4217,69,8514.076
 8414.2713510.8918344.4622668.4533095.9432873.51
River Rch & RM=4217,69,8310.641
 8415.8113513.45   18348 22672.933102.4432879.27
River Rch & RM=4217,69,7850.614
 8449.3613568.9218424.7922769.3433243.2433004.17
River Rch & RM=4217,69,7476.805
 8455.0313578.2918437.7722785.6433267.0433025.29
River Rch & RM=4217,69,7345.291
 8456.3913580.5518440.9122789.5833272.79 33030.4
River Rch & RM=4217,69,6435.842
 8484.1513626.4818504.5322869.52 33389.533133.98
River Rch & RM=4217,69,5659.732
 8611.0313836.3618795.2123234.6333922.5733606.17
River Rch & RM=4217,69,5385.923
 8616.31 13845.118807.3223249.8633944.7933625.87
River Rch & RM=4217,69,4924.822
    862613861.1618829.5823277.8433985.6533662.07
River Rch & RM=4217,69,4423.366
 8634.6713875.5218849.4923302.8634022.1833694.45
River Rch & RM=4217,69,3773.259
 8674.3813941.3218940.7223417.5734189.6533842.87
River Rch & RM=4217,69,3475.434
 8677.9313947.22 18948.923427.8534204.6633856.18
River Rch & RM=4217,69,2834.945
 8736.2114044.1119083.5223597.4434452.26 34076.4
River Rch & RM=4217,69,2204.949
 8764.3214090.7719148.2823678.9334571.2334181.88
River Rch & RM=4217,69,2099.747
 8764.82 14091.619149.4423680.3934573.3734183.77
River Rch & RM=4217,69,1627.639
 8767.6714096.33   1915623688.6634585.45 34194.5
River Rch & RM=4217,69,1178.977
 8810.1814167.3919255.0423813.76 34768.134357.82
River Rch & RM=4217,69,941.0899
 8819.4614182.9319276.7323841.1934808.1434393.72
River Rch & RM=4217,69,843.3199
 8820.1214184.0319278.2723843.1334810.9734396.23
River Rch & RM=4217,69, 735.274
 8820.9514185.4119280.1923845.55 34814.534399.38
River Rch & RM=4217,69,587.4185
 8821.4414186.2319281.33   2384734816.6234401.27
River Rch & RM=4217,69,228.5948
 8838.0214213.9319319.9323895.7534887.7934464.84
Boundary for River Rch & Prof#=4217,69,1
Up Type= 0
Dn Type= 2
Boundary for River Rch & Prof#=4217,69,2
Up Type= 0
Dn Type= 2
Boundary for River Rch & Prof#=4217,69,2
Up Type= 0
Dn Type= 2
Boundary for River Rch & Prof#=4217,69,2
Up Type= 0
Dn Type= 2
Boundary for River Rch & Prof#=4217,69,2
Up Type= 0
Dn Type= 2
Boundary for River Rch & Prof#=4217,69,2
Up Type= 0
Dn Type= 2

--- 4217_ras.g01 (geometry) ---

Geom Title=4217
Program Version=4.10

River Reach=4217,69
Reach XY= 30
421105.948662877792870.725579336420695.358385116793282.183912665
420475.740329564793204.058912665420741.799357325792668.468634889
420450.566718429792640.256829336420201.434773982792977.496412665
420010.462551773792926.715162665420040.034311146792537.826273784
 419482.39542225792895.465162665418996.978755534792588.520718217
418646.284311026792798.937384903418567.117644489 792189.21516268
417971.978755593792869.770718232417382.395422131792655.187384903
416930.485699952792987.913079336416713.262030929792123.756539986
415936.699530929792084.694039986415788.782864392792412.819039986
415246.595364273792232.610706657414571.262609631791593.161198542
414509.413651317791194.940712437413668.050804108790044.550087452
412601.384137422790609.046615213411702.946637422790786.129948542
411310.585526317791995.331337452410388.710526377791894.636893004
409706.418859631 792117.72717078408702.425804079792129.413368687
407517.529970765792803.024479792405779.303188503792728.100175455

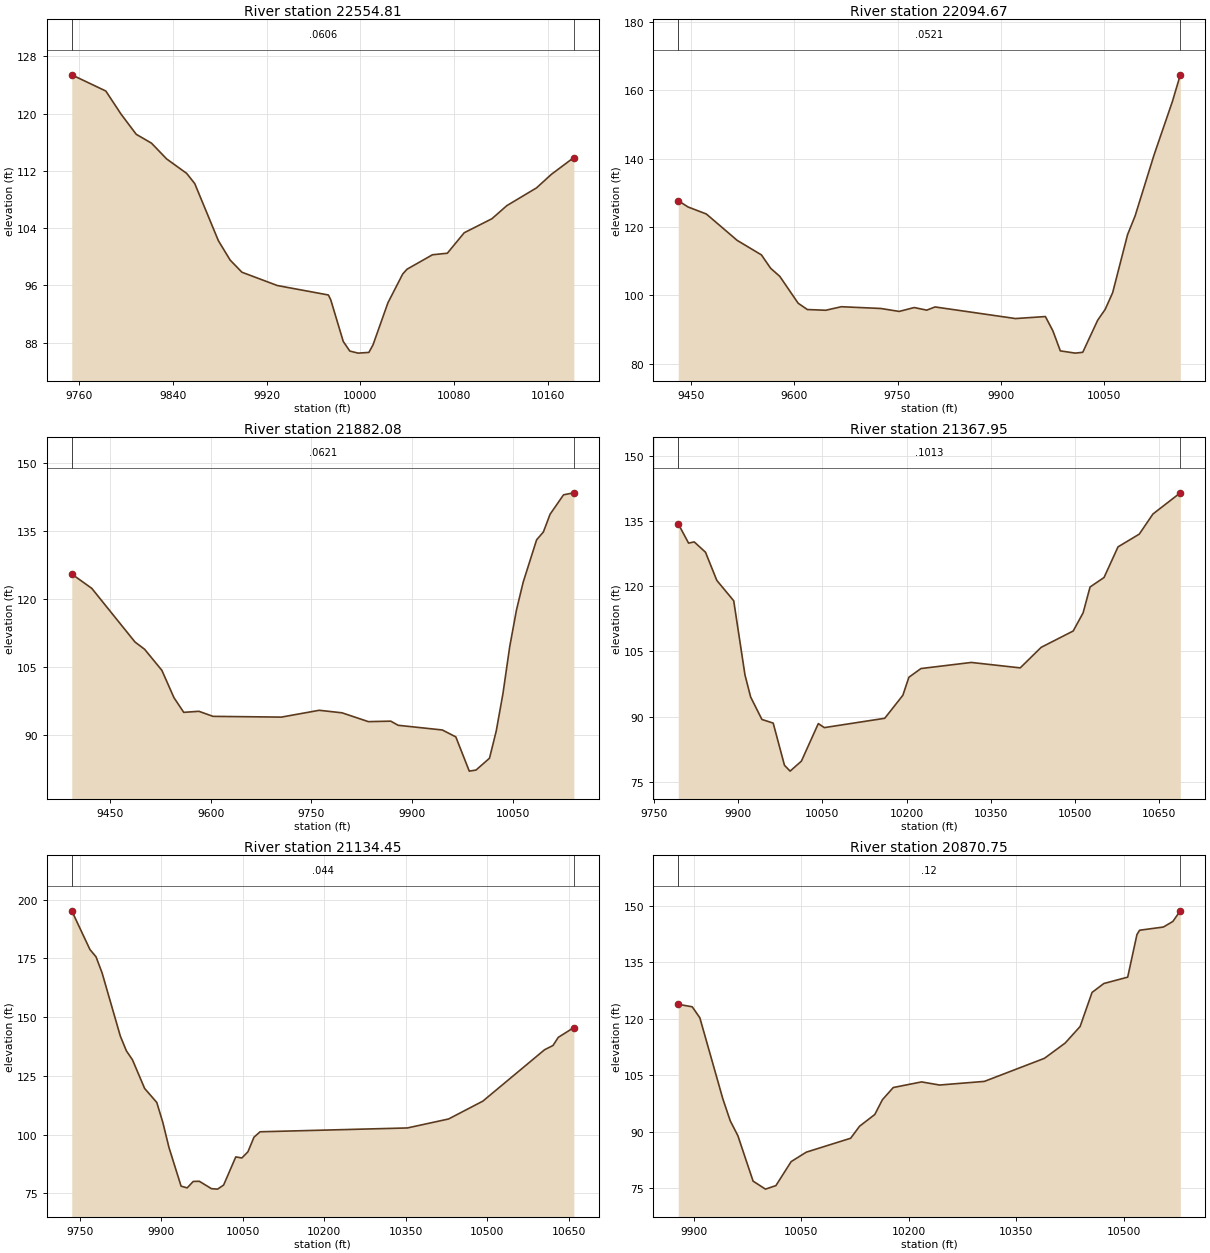
Type RM Length L Ch R = 1 ,22554.81,460.140800,460.140800,460.140800
XS GIS Cut Line= 4
 420988.15723601792842.629565939 420925.65723601792918.150399283
420934.771819383793000.181649253421130.084319353793152.525399268
#Sta/Elev= 30
9753.852125.4265 9782.89123.1645 9795.87119.93619808.851117.11169821.831115.8777
9834.812 113.6659851.881111.64549858.773110.21759878.896102.24679888.95899.52872
9899.01997.829599929.20495.971159972.75494.65126 9974.7793.973989985.43688.15269
 9991.0386.810119998.11886.5222510007.2986.62272 10010.8  87.67510023.5593.56505
10036.1697.5870510039.8198.2517910061.53100.272610074.21100.487810088.59103.3478
10112.26105.311810124.94107.138310150.31109.625510162.99111.520310182.12 113.863
#Mann= 3 , 0 , 0
9753.852  0.0606       09753.852  0.0606       010182.12  0.0606       0
#XS Ineff= 2 , 0
       0                               0
Bank Sta=9753.852,10182.12
Exp/Cntr=0.3,0.1

Type RM Length L Ch R = 1 ,22094.67,212.589800,212.589800,212.589800
XS GIS Cut Line= 3
420981.646819383792824.400399253420670.448902696793177.264982581
 420570.18848601793415.546232596
#Sta/Elev= 30
9431.607127.6807 9445.74125.83929472.407123.77839517.249116.04419552.407111.8021
 9565.74107.89169579.073105.5148 9605.7497.651489619.07395.80528 9645.7495.58991
9668.43596.62605 9725.7496.113689752.40795.252049774.26596.386119792.40795.62088
9804.50296.560479921.33593.163939964.73193.75135 9975.58 89.5722 9986.4383.69916
10008.1383.0408310018.9883.2884210040.6892.6963510051.5295.8533510062.37100.7406
10084.07117.765910094.92123.172710122.42141.027710149.17 156.74110160.61164.5204
#Mann= 3 , 0 , 0
9431.607  0.0521       09431.607  0.0521       010160.61  0.0521       0
#XS Ineff= 2 , 0
       0 9871.65                       0
Bank Sta=9431.607,10160.61
Exp/Cntr=0.3,0.1

Type RM Length L Ch R = 1 ,21882.08,514.133400,514.133400,514.133400
XS GIS Cut Line= 5
 420953.00098601792821.796232581420893.105152696792896.014982596
420670.448902696793106.952482581 420542.84473601793168.150399268
 420339.71973601793181.171232596
#Sta/Elev= 30
9393.359125.53169423.176122.36989487.427110.54989501.796108.93869527.446104.3006
9545.41798.282069559.95795.040399582.54695.266579603.57894.15484 9705.3693.98802
9761.62195.49415 9795.4494.938479834.75592.989519868.02793.095949879.11792.18461
9944.82191.150629964.86389.626619984.90482.078549994.92482.3146410014.9784.92017
10024.9990.9050910035.0199.1793710045.03109.479210055.05117.551310065.07123.7265
10085.11133.078410095.13134.795510105.15138.718710125.19143.0012 10140.5143.4368
#Mann= 3 , 0 , 0
9393.359  0.0621       09393.359  0.0621       0 10140.5  0.0621       0
#XS Ineff= 2 , 0
       09786.002                       0
Bank Sta=9393.359,10140.5
Exp/Cntr=0.3,0.1

Type RM Length L Ch R = 1 ,21367.95,233.496500,233.496500,233.496500
XS GIS Cut Line= 4
420993.365569353792790.546232581420744.667652696792767.108732581
 420550.65723601792843.931649268420291.542652696793194.192065939
#Sta/Elev= 30
9793.212134.40999811.659129.95069821.703130.23219841.792 127.8529861.881 121.375
9892.014116.67619912.102 99.58899922.14794.518759942.23589.334689962.32488.50479
9982.41278.787979992.45777.4391610012.5579.7418210042.6888.3875710053.4187.46164
10160.9689.6079110193.2394.9007810203.9999.05802 10225.5101.0652 10315.2102.4705
10402.27101.220210439.59105.952710496.59109.712810514.23113.885510526.66 119.848
10551.54122.037810576.42129.086510614.29132.027210638.61136.655710687.37 141.536
#Mann= 3 , 0 , 0
9793.212  0.1013       09793.212  0.1013       010687.37  0.1013       0
#XS Ineff= 2 , 0
       0                               0
Bank Sta=9793.212,10687.37
Exp/Cntr=0.3,0.1

Type RM Length L Ch R = 1 ,21134.45,263.705200,263.705200,263.705200
XS GIS Cut Line= 3
420760.292652696 792415.11220482420582.341263801792771.014982596
 420261.59473601793187.681649253
#Sta/Elev= 30
9735.524195.1989 9768.94 178.742 9780.12 175.6419791.301168.80879824.842141.9172
9836.022135.62779847.202131.80939869.563119.63059891.924113.67249903.104105.1385
9914.28494.574069936.64578.061389947.82577.317889959.00680.062449970.18680.12986
9992.54776.9826910003.7376.7889510014.91 78.526810037.2790.5063410048.4590.04214
10059.6392.6693310070.8198.8939510081.99101.1854   10353102.816910428.72106.6281
10491.82114.2236 10605.4136.092110620.89137.898210630.63141.368610659.26145.5295
#Mann= 3 , 0 , 0
9735.524   0.044       09735.524   0.044       010659.26   0.044       0
#XS Ineff= 2 , 0
       0                               0
Bank Sta=9735.524,10659.26
Exp/Cntr=0.3,0.1

Type RM Length L Ch R = 1 ,20870.75,434.552800,434.552800,434.552800
XS GIS Cut Line= 3
420354.042652696792566.587899253 420464.71973601792876.483732581
420240.761402696793173.358732596
#Sta/Elev= 30
9878.214123.88039897.765123.21159908.383120.29249940.52498.711819950.85892.87415
9961.47788.933239982.71476.852529999.98974.7211810014.5775.6573310035.8182.03231
10057.0484.5574510118.9288.2531310131.3791.4506710152.6194.5637410163.23 98.4914
10178.38101.739910217.95103.2378   10243 102.40810305.63103.375810389.47109.5113
10418.37113.563610439.28117.976410455.95127.037310472.49129.4144 10505.7131.0991
10518.58142.3979 10522.3143.574210555.51144.424510568.69145.902410579.16148.7369
#Mann= 3 , 0 , 0
9878.214    0.12       09878.214    0.12       010579.16    0.12       0
#XS Ineff= 2 , 0
       0                               0
Bank Sta=9878.214,10579.16
Exp/Cntr=0.3,0.1

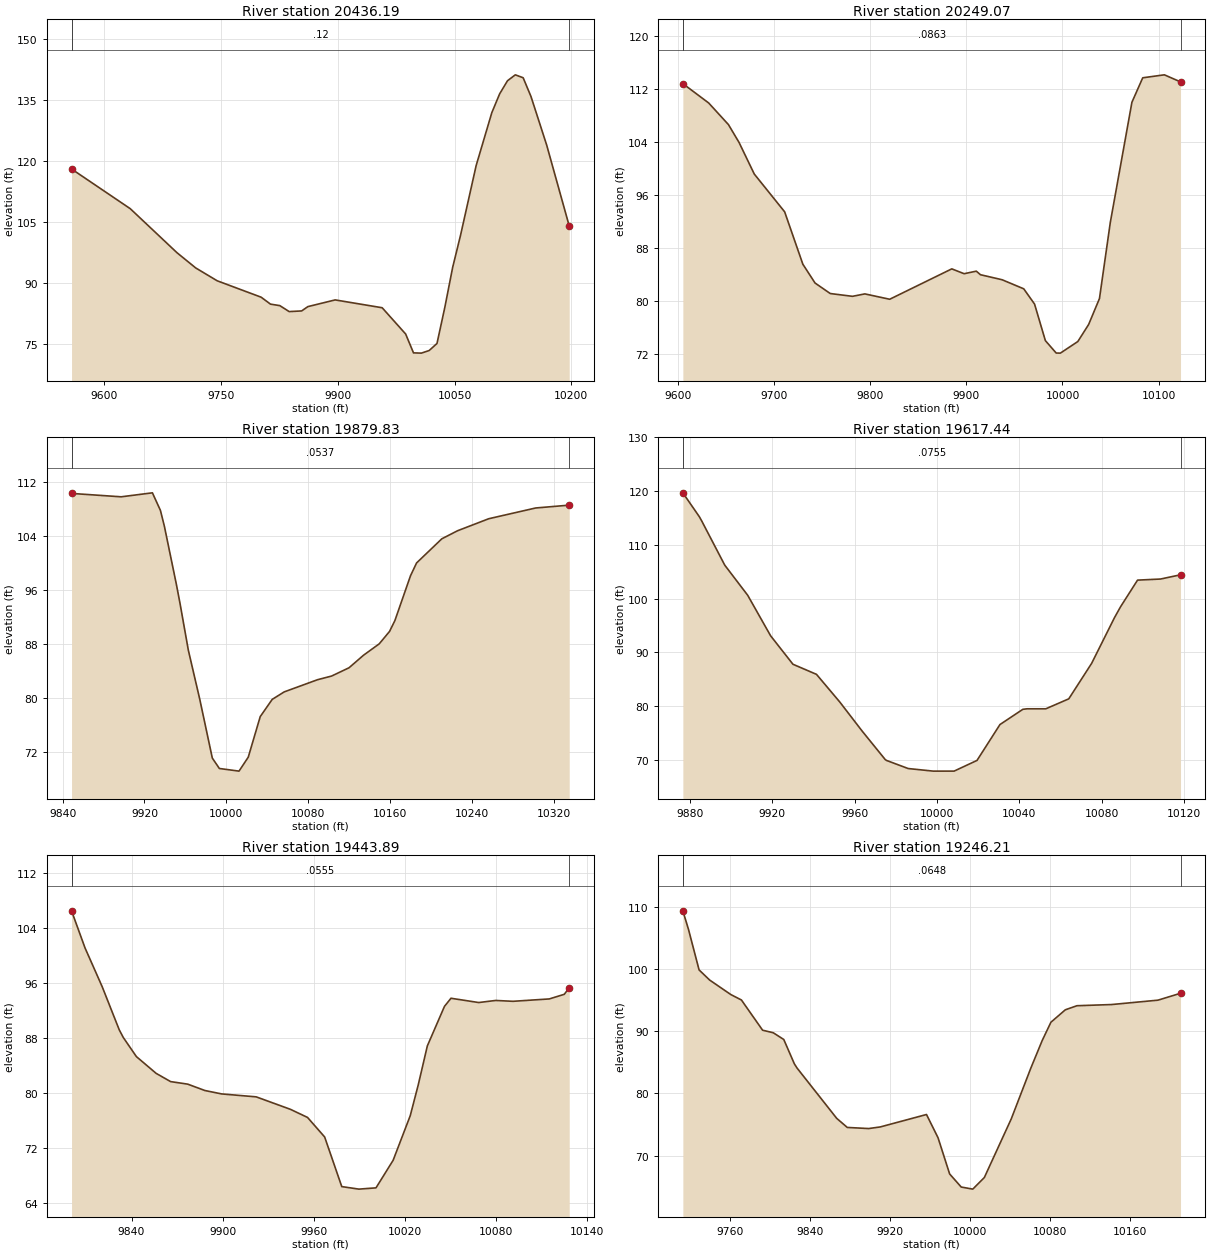
Type RM Length L Ch R = 1 ,20436.19,187.122600,187.122600,187.122600
XS GIS Cut Line= 3
420328.435013801792582.212899253420143.973208278792859.990677029
420111.421124935793163.810121477
#Sta/Elev= 30
9558.265118.00099633.635108.25289693.65697.438089717.66493.703459745.24290.54492
9801.692 86.51559813.69784.810989825.70184.442529837.70582.979069853.70283.13941
9861.71384.19993 9896.75  85.8479957.09383.923979987.26577.467689997.32272.84124
10007.3872.7780310017.4473.4165710027.49 75.151710037.5584.0186210047.6193.84558
10057.67 101.68510077.78118.852510097.89131.833410107.95136.455710118.01139.6709
10128.07 141.12510138.12140.401110148.18135.7972 10168.3123.886810197.27104.0055
#Mann= 3 , 0 , 0
9558.265    0.12       09558.265    0.12       010197.27    0.12       0
#XS Ineff= 2 , 0
       0                               0
Bank Sta=9558.265,10197.27
Exp/Cntr=0.3,0.1

Type RM Length L Ch R = 1 ,20249.07,369.237700,369.237700,369.237700
XS GIS Cut Line= 3
420272.011402696792608.254565924420078.869041592792844.799704805
419890.066958249 792942.45595482
#Sta/Elev= 30
9604.915  112.769631.813109.83979652.354106.58059663.435103.87759679.24699.11756
9710.86893.413749729.81485.505749742.49182.672229758.30281.084789781.45580.66127
9794.36581.029219820.185 80.21999884.79284.805159897.645  84.0759910.29784.46015
9914.65283.923479937.16983.163999959.68681.796659970.94579.489729982.20373.97611
9993.46272.104569997.79872.0901310015.9873.8404310027.2476.41498 10038.580.32958
10049.7591.7902510072.27109.946710083.53113.640810106.05114.089310122.86113.0221
#Mann= 3 , 0 , 0
9604.915  0.0863       09604.915  0.0863       010122.86  0.0863       0
#XS Ineff= 2 , 0
       0                               0
Bank Sta=9604.915,10122.86
Exp/Cntr=0.3,0.1

Type RM Length L Ch R = 1 ,19879.83,262.394300,262.394300,262.394300
XS GIS Cut Line= 3
420252.480152696792499.747621492420035.466263831792632.126093715
419883.556541622792807.907343701
#Sta/Elev= 30
9848.708110.26049897.199109.75929927.752110.34879935.605107.74789939.466105.4008
9951.17996.821289954.80893.947559962.89387.06333 9974.0179.84377 9986.32 71.1153
9993.21369.5744810012.42 69.183810021.4671.2489410033.1777.2492910044.8979.79667
 10056.680.9037210089.2382.7077910102.9183.2460710119.9384.4678610134.2186.33415
 10149.588.0109710159.5889.84601 10164.891.4488310180.09 98.087110186.0199.97681
10210.68103.546410225.97104.732510256.56106.516510302.44108.106910335.24108.5257
#Mann= 3 , 0 , 0
9848.708  0.0537       09848.708  0.0537       010335.24  0.0537       0
#XS Ineff= 2 , 0
       0                               0
Bank Sta=9848.708,10335.24
Exp/Cntr=0.3,0.1

Type RM Length L Ch R = 1 ,19617.44,173.549900,173.549900,173.549900
XS GIS Cut Line= 2
419831.473208249792486.726788163419937.810013801792703.740677044
#Sta/Elev= 27
9876.588119.67359884.603115.22649885.801114.40579896.937106.21989908.073100.6211
9919.20993.077569930.056 87.78449941.48185.908139952.78380.769989963.75375.30658
9974.88970.046089975.50969.892869986.02568.386599998.23567.90749 10008.367.90866
10019.4369.8990410030.5776.57156 10041.779.4082210043.6979.4976810052.8479.50022
10063.9881.3521110075.1187.9683110086.2596.5010510089.1498.4866810097.38 103.435
10108.52 103.63710118.25104.4266
#Mann= 3 , 0 , 0
9876.588  0.0755       09876.588  0.0755       010118.25  0.0755       0
#XS Ineff= 2 , 0
       0                               0
Bank Sta=9876.588,10118.25
Exp/Cntr=0.3,0.1

Type RM Length L Ch R = 1 ,19443.89,197.678400,197.678400,197.678400
XS GIS Cut Line= 2
419649.181541592792517.108732596419801.091263801792807.907343701
#Sta/Elev= 30
9800.477106.5186 9809.38101.10839820.66295.482859831.94489.185229834.64188.06057
9843.22785.298659856.238 82.85929865.79181.658299877.07381.288319888.35680.36319
9899.43379.864949922.202 79.43869944.76777.623319956.04976.442629967.33173.59924
9978.61466.375599989.89666.0066410001.1866.1919310012.4670.1990910023.7476.68751
10029.0281.1725510035.0286.8496510046.3192.6069610050.6193.7912210068.8793.16842
10080.1593.4715810091.4493.3463510115.4193.6926710125.2894.3653410128.5695.30012
#Mann= 3 , 0 , 0
9800.477  0.0555       09800.477  0.0555       010128.56  0.0555       0
#XS Ineff= 2 , 0
       0                               0
Bank Sta=9800.477,10128.56
Exp/Cntr=0.3,0.1

Type RM Length L Ch R = 1 ,19246.21,363.811600,363.811600,363.811600
XS GIS Cut Line= 3
419592.757930458792549.660815939419531.994041592792723.271927029
419690.414180487792994.539288148
#Sta/Elev= 30
9712.718109.31669718.375106.32899728.96999.827259739.56498.196869760.75495.86925
9771.349  94.9969792.53890.146659803.13389.740549813.72888.654129824.32384.74392
9827.01484.067839866.70275.991569877.29774.530489898.65774.353429910.23774.61017
9956.55976.608729968.13972.86555 9979.7267.06296  9991.364.9626410002.8864.62603
10014.4666.4926110041.4275.9186910060.7883.9841910072.3688.4899510081.08 91.4257
10095.5293.42487 10107.194.0764410141.85 94.267710188.1794.9698310210.7996.07581
#Mann= 3 , 0 , 0
9712.718  0.0648       09712.718  0.0648       010210.79  0.0648       0
#XS Ineff= 2 , 0
       0                               0
Bank Sta=9712.718,10210.79
Exp/Cntr=0.3,0.1

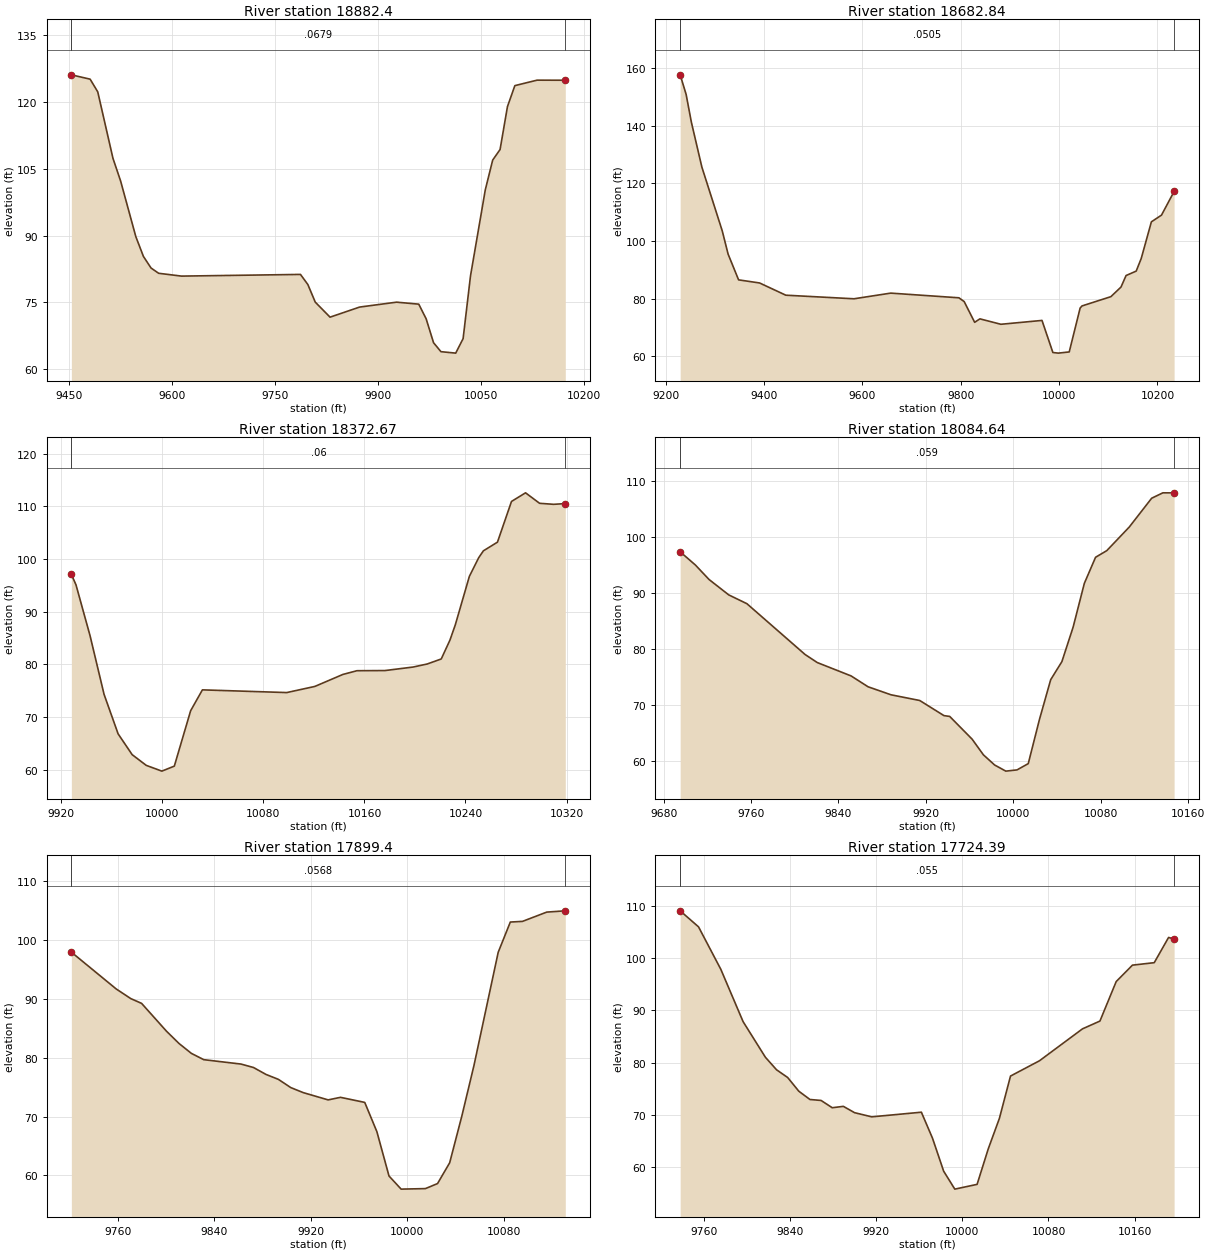
Type RM Length L Ch R = 1 , 18882.4,199.560000,199.560000,199.560000
XS GIS Cut Line= 3
419629.650291592792488.896927029419349.702374935792623.445538148
419197.792652696793003.219843701
#Sta/Elev= 30
9452.897126.05639480.247125.08159491.342122.23919513.532107.30529524.627102.2502
9546.81789.745489557.91285.299619569.00782.704549580.10281.523519613.38780.89181
9786.71581.268539797.48578.996969808.25575.050929829.79671.679419872.87773.94361
9926.72975.04464 9959.0474.59529 9969.81 71.31029980.58165.951729991.35163.93458
10012.8963.6088310023.6666.8686810034.4380.9434510055.97100.246410066.74106.9244
10077.51109.296810088.28118.931610099.05 123.63110131.37124.859210172.53 124.842
#Mann= 3 , 0 , 0
9452.897  0.0679       09452.897  0.0679       010172.53  0.0679       0
#XS Ineff= 2 , 0
       09687.505                       0
Bank Sta=9452.897,10172.53
Exp/Cntr=0.3,0.1

Type RM Length L Ch R = 1 ,18682.84,310.171100,310.171100,310.171100
XS GIS Cut Line= 4
419414.806541592792013.636510387419160.900291592792697.230260387
419069.754458249792740.633038148419110.987097144792909.903871477
#Sta/Elev= 30
9229.446157.60359241.568150.80599252.235141.1709 9273.57125.61419315.051103.4763
9326.908 95.44849348.24386.512659390.91385.43779 9444.2581.198829582.928 79.9524
9657.60181.916649796.27980.295129806.94678.989749828.28171.796259838.94972.99404
9881.61971.113629965.206 72.44849987.35761.325519998.43361.1114910020.59 61.5286
10042.7476.7316710046.5277.4700210105.2980.6921210125.8784.0218110136.1688.01651
10156.7589.5510810167.0493.9503510187.63106.630910208.21108.958710233.84117.1707
#Mann= 3 , 0 , 0
9229.446  0.0505       09229.446  0.0505       010233.84  0.0505       0
#XS Ineff= 2 , 0
       0 9724.14                       0
Bank Sta=9229.446,10233.84
Exp/Cntr=0.3,0.1

Type RM Length L Ch R = 1 ,18372.67,288.028900,288.028900,288.028900
XS GIS Cut Line= 2
418863.591263831792571.723894641 419035.03223601792923.286394641
#Sta/Elev= 30
9927.90197.093919931.54695.132899942.67285.486569953.79774.326349964.92366.82734
9976.049 62.87749987.17460.844839999.55959.7489910009.4360.6972910022.3771.22169
10031.6875.1762610098.4374.6623910120.68 75.824210142.9378.1035610154.0678.81194
10176.3178.8412410198.5679.5108410209.6980.0863310220.8181.0422510227.71 84.6253
10231.9487.5216610243.0696.7103910250.52100.286510254.19101.572110265.32103.2176
10276.44 110.94710287.57112.582710298.69110.593210309.82110.400610319.04110.5395
#Mann= 3 , 0 , 0
9927.901    0.06       09927.901    0.06       010319.04    0.06       0
#XS Ineff= 2 , 0
       0                               0
Bank Sta=9927.901,10319.04
Exp/Cntr=0.3,0.1

Type RM Length L Ch R = 1 ,18084.64,185.240500,185.240500,185.240500
XS GIS Cut Line= 4
418851.655499905792573.894033536418812.592999905792625.977366865
418678.044388801792739.909658536418630.301333249792944.987783521
#Sta/Elev= 30
9695.13397.337579709.01694.987289721.51692.395969739.559 89.63659756.22688.05454
9809.49878.961659820.624 77.52849851.57375.136689867.04873.199939888.11971.76218
9914.32670.745769936.54468.03747 9941.7767.894959962.30563.823589972.573  61.034
 9982.8459.212129993.10758.1110410003.3758.3311510013.6459.4499210023.9167.36124
10034.1874.4648610044.4477.7012310054.7183.8708410064.9891.7027310075.2596.36306
10085.5197.5491910106.05101.765310126.58106.924610136.85107.889910147.11107.8779
#Mann= 3 , 0 , 0
9695.133   0.059       09695.133   0.059       010147.11   0.059       0
#XS Ineff= 2 , 0
       0                               0
Bank Sta=9695.133,10147.11
Exp/Cntr=0.3,0.1

Type RM Length L Ch R = 1 , 17899.4,175.009000,175.009000,175.009000
XS GIS Cut Line= 4
418848.400291592792564.128408536418816.933277696792610.786394641
418658.513138831792650.933964074418469.711055487792629.232575193
#Sta/Elev= 30
 9721.3397.908169758.56791.654269770.628  90.0249779.60289.210379800.23484.49081
 9810.5582.419729820.86680.727039831.18379.654129862.13178.907979872.44778.32299
9882.76377.151329893.07976.312139903.39574.911569913.712 74.06019934.34472.82648
9944.57273.261919964.70472.40111 9974.7767.439519984.83559.906949994.90157.67778
10015.0357.76592 10025.158.6211510035.1662.1466910045.23 70.0614 10055.378.65529
10075.4397.8889910085.49103.019110095.56103.131110115.69104.707310131.08104.9244
#Mann= 3 , 0 , 0
 9721.33  0.0568       0 9721.33  0.0568       010131.08  0.0568       0
#XS Ineff= 2 , 0
       0                               0
Bank Sta=9721.33,10131.08
Exp/Cntr=0.3,0.1

Type RM Length L Ch R = 1 ,17724.39,119.157800,119.157800,119.157800
XS GIS Cut Line= 3
418881.484058946792541.135786995418568.984058976792457.281620324
418479.400725603792558.844120324
#Sta/Elev= 30
9737.739109.02859754.806  105.969775.51397.835499796.22187.816979816.928 81.0101
9827.282 78.60979837.63677.12975 9847.9974.506319858.34372.922569868.69772.73798
9879.051 71.34479889.40571.606759899.75870.401949915.755  69.6019961.88170.48957
9972.23565.505569982.58859.201389992.942 55.768510013.6556.67987   1002463.46244
10034.3669.2942810044.7177.4083210071.5980.3306210111.5986.4420510127.79 87.9295
 10142.9 95.487310158.0298.6347710178.2699.1052410191.59103.935710196.72103.6239
#Mann= 3 , 0 , 0
9737.739   0.055       09737.739   0.055       010196.72   0.055       0
#XS Ineff= 2 , 0
       0                               0
Bank Sta=9737.739,10196.72
Exp/Cntr=0.3,0.1

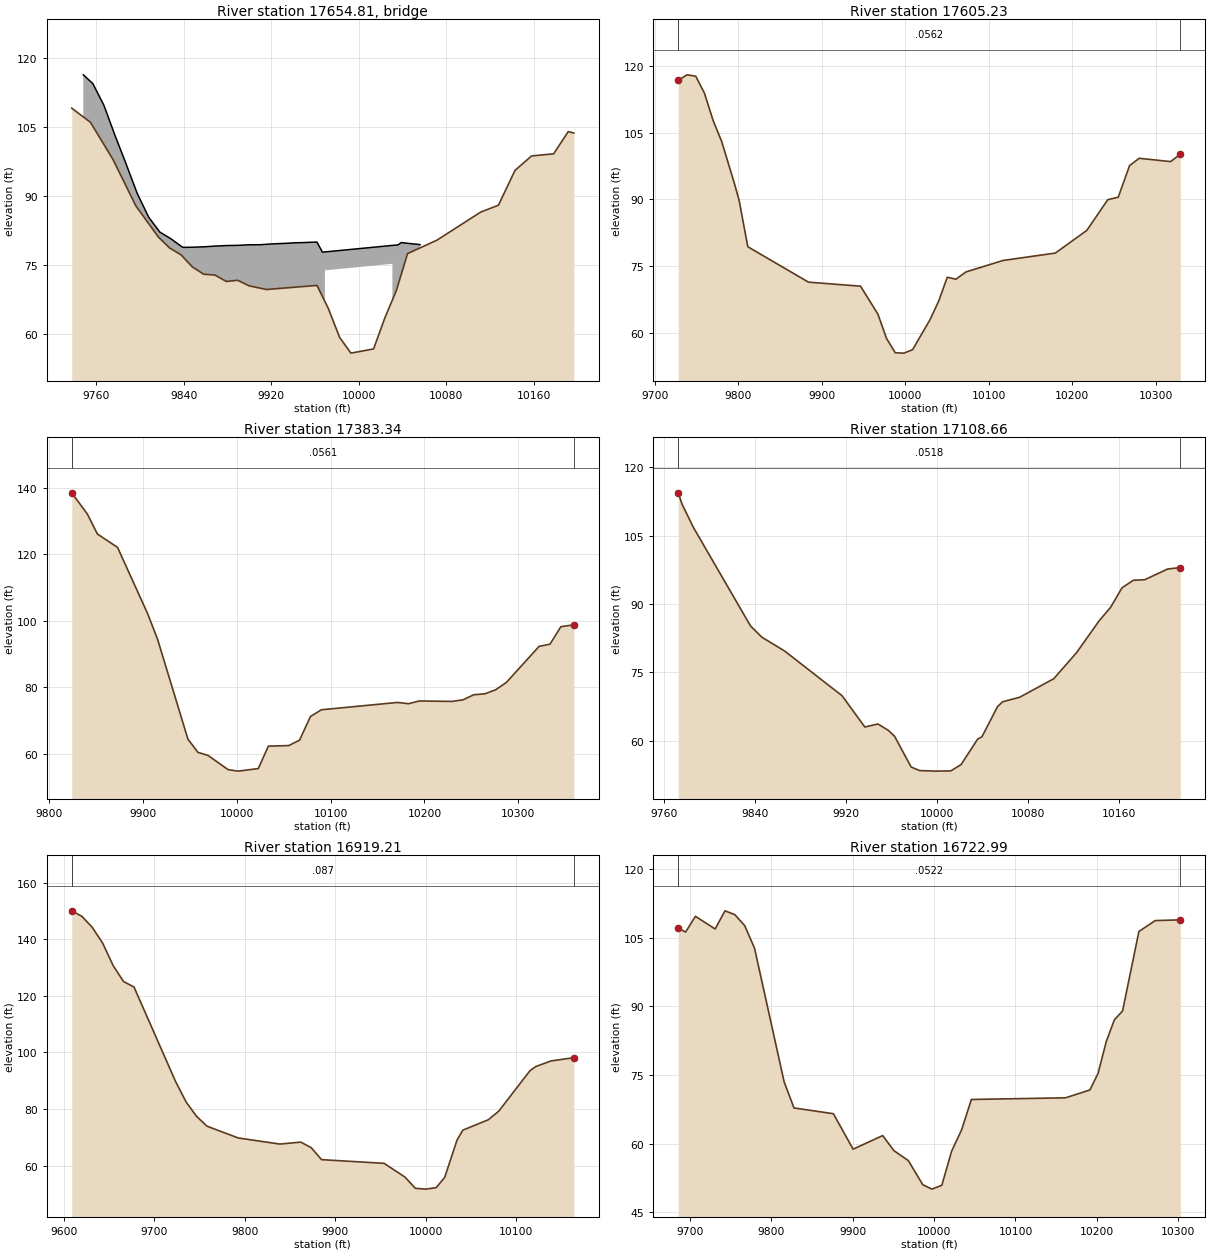
Type RM Length L Ch R = 3 ,17654.81,,,
BEGIN DESCRIPTION:
END DESCRIPTION:
Bridge Culvert--1,0,-1,-1, 0
Deck Dist Width WeirC Skew NumUp NumDn MinLoCord MaxHiCord MaxSubmerge Is_Ogee
44.323000,30.511800,2.6,0, 37, 37, , , 0.95, 0, 0,0,,
 9748.28 9757.00 9767.20 9777.41 9787.62 9790.40 9797.82 9808.03 9818.23 9828.44
 9838.65 9840.42 9848.85 9859.06 9869.26 9879.47 9889.68 9890.44 9899.88 9910.09
 9920.29 9930.50 9934.35 9938.44 9940.88 9951.35 9961.83 9966.93 9969.16 9969.16
10030.8410030.8410035.9610039.0210045.6410055.4110056.10
  116.28  114.37  109.61  103.01   96.77   95.00   90.36   85.34   82.09   80.62
   78.85   78.76   78.80   78.89   79.05   79.16   79.20   79.21   79.33   79.34
   79.51   79.61   79.65   79.71   79.75   79.82   79.92   77.72   77.77   77.77
   79.19   79.19   79.30   79.81   79.62   79.39   79.35
 -883.72 -885.63 -890.39 -896.99 -903.23 -905.00 -909.64 -914.66 -917.91 -919.38
 -921.15 -921.24 -921.20 -921.11 -920.95 -920.84 -920.80 -920.79 -920.67 -920.66
 -920.49 -920.39 -920.35 -920.29 -920.25 -920.18 -920.08 -922.28 -922.23   73.77
   75.19 -920.81 -920.70 -920.19 -920.38 -920.61 -920.65
 9748.28 9757.00 9767.20 9777.41 9787.62 9790.40 9797.82 9808.03 9818.23 9828.44
 9838.65 9840.42 9848.85 9859.06 9869.26 9879.47 9889.68 9890.44 9899.88 9910.09
 9920.29 9930.50 9934.35 9938.44 9940.88 9951.35 9961.83 9966.93 9969.16 9969.16
10030.8410030.8410035.9610039.0210045.6410055.4110056.10
  116.28  114.37  109.61  103.01   96.77   95.00   90.36   85.34   82.09   80.62
   78.85   78.76   78.80   78.89   79.05   79.16   79.20   79.21   79.33   79.34
   79.51   79.61   79.65   79.71   79.75   79.82   79.92   77.72   77.77   77.77
   79.19   79.19   79.30   79.81   79.62   79.39   79.35
 -883.72 -885.63 -890.39 -896.99 -903.23 -905.00 -909.64 -914.66 -917.91 -919.38
 -921.15 -921.24 -921.20 -921.11 -920.95 -920.84 -920.80 -920.79 -920.67 -920.66
 -920.49 -920.39 -920.35 -920.29 -920.25 -920.18 -920.08 -922.28 -922.23   73.77
   75.19 -920.81 -920.70 -920.19 -920.38 -920.61 -920.65
BR Coef=-1 , 0 , 0 ,, 0 ,,,0.8,0,1,0,
WSPro=,,,, 1 ,,,, 0 ,,,, 0 ,,,,-1 ,-1 ,-1 , 0 , 0 , 0 , 0 , 0
BC Design=,, 0 ,, 0 ,,,,,,

Type RM Length L Ch R = 1 ,17605.23,221.895300,221.895300,221.895300
XS GIS Cut Line= 3
418925.234058946792433.323286995418593.463225603792339.573286995
 418438.25489226792544.260786995
#Sta/Elev= 30
9728.013116.83089738.648118.0202 9749.04117.70319759.431113.88879769.823107.7413
9780.214102.94089795.39793.517869800.99889.756849811.38979.32126 9884.1371.34938
 9946.4870.445219967.263  64.1659977.65458.676169988.04655.454089998.43855.37636
10008.8356.1512310029.6162.86494   1004067.03138 10050.472.4572510060.7972.02087
10072.78 73.654610117.2476.2327510179.9877.9043910217.6383.0067810242.7389.91216
10255.2890.4711610268.8497.5734310280.3899.2362510318.0398.4840310329.65100.1537
#Mann= 3 , 0 , 0
9728.013  0.0562       09728.013  0.0562       010329.65  0.0562       0
#XS Ineff= 2 , 0
       0                               0
Bank Sta=9728.013,10329.65
Exp/Cntr=0.3,0.1

Type RM Length L Ch R = 1 ,17383.34,274.677700,274.677700,274.677700
XS GIS Cut Line= 3
418689.145904034792029.493897244418606.680626243792242.167508364
418450.430626243792506.924452811
#Sta/Elev= 30
9823.859138.5196 9840.49132.14299851.215126.13389872.666122.11919904.843102.1534
9915.56894.322429947.74564.45647 9958.4760.464849969.19559.548939990.64655.27229
10001.3754.8291110022.8255.6000510033.5562.3431410055.2762.5116210066.8664.15028
10078.4771.2561810090.08 73.279410171.3775.4876310182.9875.1043310194.5975.92598
10229.4275.7953710241.0476.2640110252.65 77.796910264.2678.0638710275.8779.26822
10287.4881.5151110322.3292.3527310333.9393.0020810345.5498.2669410359.3998.82553
#Mann= 3 , 0 , 0
9823.859  0.0561       09823.859  0.0561       010359.39  0.0561       0
#XS Ineff= 2 , 0
       0                               0
Bank Sta=9823.859,10359.39
Exp/Cntr=0.3,0.1

Type RM Length L Ch R = 1 ,17108.66,189.452300,189.452300,189.452300
XS GIS Cut Line= 4
418337.549597174792111.726788148418354.910708249792281.865677044
418438.244041592792359.990677044418434.771819353792516.240677044
#Sta/Elev= 30
9772.163114.40119775.453111.95489785.505106.80429835.76585.161949845.81782.68896
9865.92179.63481 9916.1869.866829936.28462.987969947.76863.649529957.01562.23689
9962.38960.96561 9977.0154.18843 9984.4353.425749998.13753.2984510011.8453.35013
10020.8754.72483 10035.560.3368810039.2660.8435310052.9767.4662610057.4168.52322
10072.4369.5223610102.43 73.586210122.4479.3054510142.4486.3393710152.45  89.277
10162.45 93.551610172.4595.2041510182.4595.3215310202.4697.66228 10213.797.99685
#Mann= 3 , 0 , 0
9772.163  0.0518       09772.163  0.0518       0 10213.7  0.0518       0
#XS Ineff= 2 , 0
       0                               0
Bank Sta=9772.163,10213.7
Exp/Cntr=0.3,0.1

Type RM Length L Ch R = 1 ,16919.21,196.220300,196.220300,196.220300
XS GIS Cut Line= 2
417935.303503394792270.302453667418417.074336737792545.910092548
#Sta/Elev= 30
9608.888150.00889620.059148.0687 9631.58144.16669643.101138.55959654.621130.6801
9666.142125.01819677.663123.10519723.74689.639479735.26682.495859746.78777.42943
9758.308 73.9488 9792.8769.771099838.95367.613129861.99468.300039873.51566.36408
9885.035  62.106 9954.1660.810129977.20155.965529988.72251.9779210000.2451.69551
10011.7652.2264510021.12  55.812 10034.869.0468810041.2672.5417710069.3776.20906
10080.8979.2264810115.4593.5532410121.8194.9905810138.4996.9710810163.9298.13199
#Mann= 3 , 0 , 0
9608.888   0.087       09608.888   0.087       010163.92   0.087       0
#XS Ineff= 2 , 0
       0                               0
Bank Sta=9608.888,10163.92
Exp/Cntr=0.3,0.1

Type RM Length L Ch R = 1 ,16722.99,191.092500,191.092500,191.092500
XS GIS Cut Line= 3
417887.560447872792435.233009204418258.654197842792689.139259219
 418425.75489226792702.160092548
#Sta/Elev= 30
9685.375107.15189694.389106.23059706.506109.68679730.739 106.9139742.856110.8801
9754.973110.0458 9767.09107.64449779.206102.71049815.55673.545049827.673 67.8297
 9876.1466.570989900.37358.824459936.72361.793239950.59858.498789968.307 56.3253
9986.01651.063599997.30750.0998910009.4250.9373710021.54 58.414710033.6663.00395
10045.7769.6806810161.4470.0410910191.5371.7561410201.57 75.4052 10211.682.34039
10221.6387.0902110231.6689.0221310251.72106.374110271.78  108.7510302.63108.9065
#Mann= 3 , 0 , 0
9685.375  0.0522       09685.375  0.0522       010302.63  0.0522       0
#XS Ineff= 2 , 0
       0                10098.18       0
Bank Sta=9685.375,10302.63
Exp/Cntr=0.3,0.1

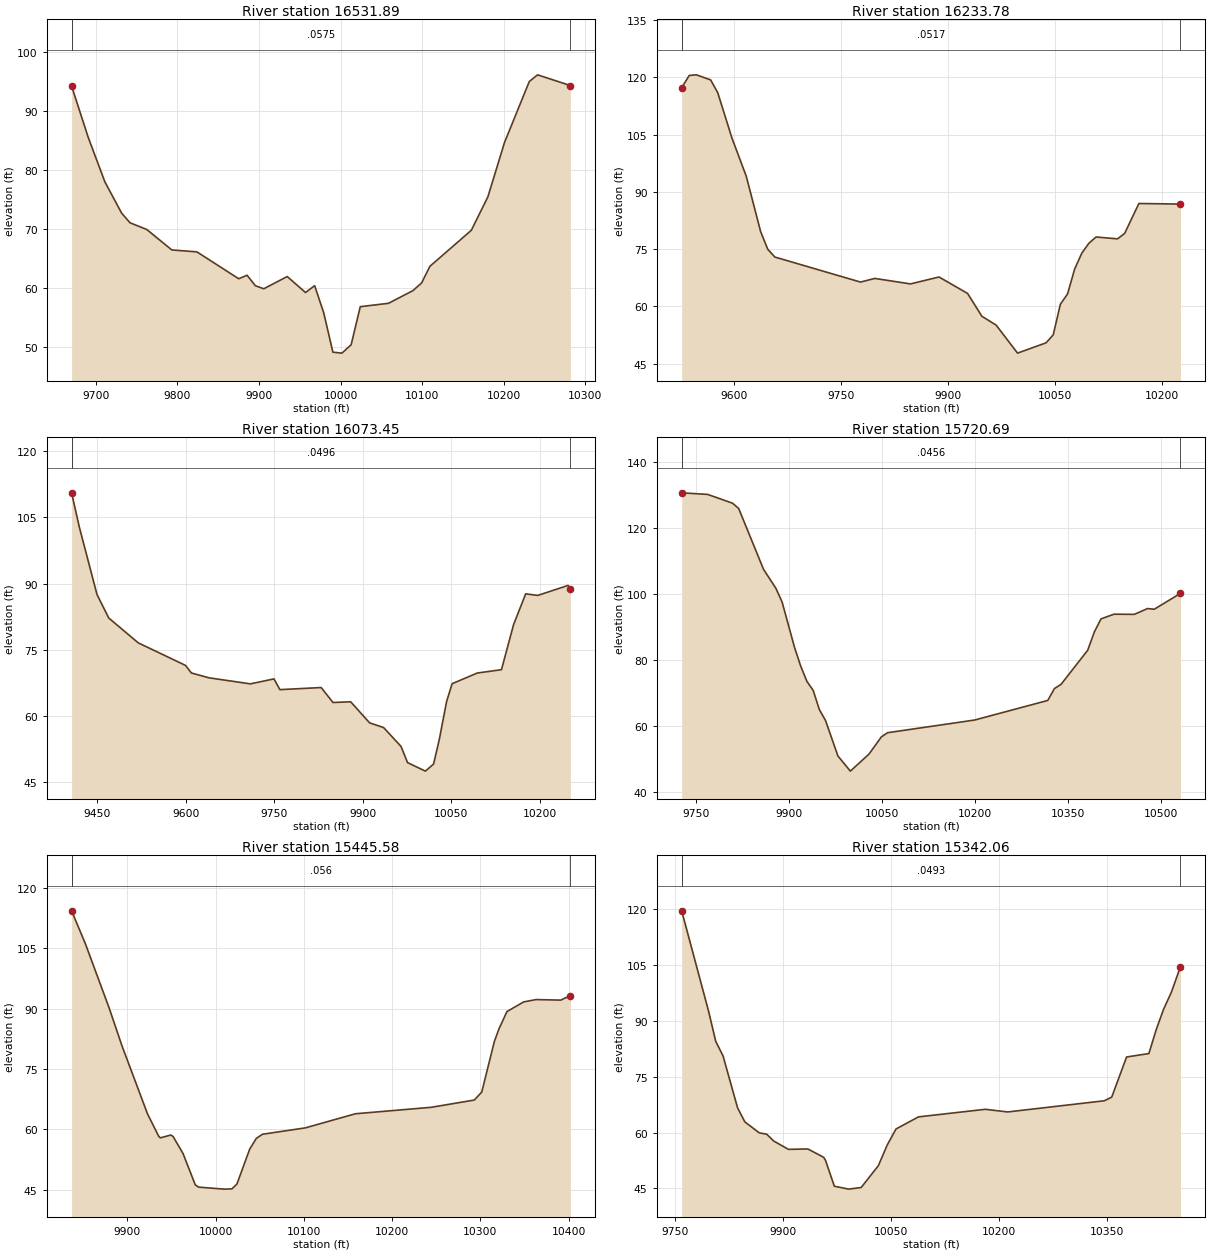
Type RM Length L Ch R = 1 ,16531.89,298.112300,298.112300,298.112300
XS GIS Cut Line= 4
417907.091697842792485.146203667417961.345170081792728.201759204
418078.532670081792786.795509219418117.595170081793014.660092562
#Sta/Elev= 30
9670.41394.178849690.75685.494639711.24877.91977 9731.7472.631889741.98670.99678
9762.47869.864839793.217 66.39189823.95566.063819875.18661.507739885.43262.10028
9895.67860.317749905.92459.806629934.65261.878479957.07859.170059968.25860.33003
9979.37355.736939990.61949.0515910001.7348.8903110012.9850.3046510024.1656.76618
10058.79 57.341110088.7559.4944510099.3860.8050110109.5263.6166910160.2569.72408
10180.5475.3904910200.8484.5787410231.2794.9526810241.4296.0907210281.6694.27261
#Mann= 3 , 0 , 0
9670.413  0.0575       09670.413  0.0575       010281.66  0.0575       0
#XS Ineff= 2 , 0
       09748.917                       0
Bank Sta=9670.413,10281.66
Exp/Cntr=0.3,0.1

Type RM Length L Ch R = 1 ,16233.78,160.335900,160.335900,160.335900
XS GIS Cut Line= 2
417824.626420051792374.469120324 417800.75489226793073.253842548
#Sta/Elev= 30
9527.151117.30019537.688 120.5219547.694120.68739567.705119.36039577.711115.9987
9597.723104.05869617.73594.068449637.74679.643419647.75274.987879657.75872.92819
9777.82866.37178 9797.8467.327659847.86965.889759887.89267.701139927.91563.39291
9947.92757.409429967.93955.096859997.95647.7479410037.9850.4515510047.9952.54298
10057.9960.56689   1006863.23394   1007869.7771810088.0173.9473810098.0176.55545
10108.0278.1860410138.04 77.698410148.0479.1067310168.0686.9623110226.3486.80851
#Mann= 3 , 0 , 0
9527.151  0.0517       09527.151  0.0517       010226.34  0.0517       0
#XS Ineff= 2 , 0
       0 9706.42                       0
Bank Sta=9527.151,10226.34
Exp/Cntr=0.3,0.1

Type RM Length L Ch R = 1 ,16073.45,352.756900,352.756900,352.756900
XS GIS Cut Line= 4
417713.949336708792292.003842548417696.588225633792793.305925876
417635.824336708792923.514259204417681.397253394793118.826759204
#Sta/Elev= 30
9406.437 110.5989419.441102.87299449.45987.529119469.47182.176429519.50176.53913
9599.54971.427089609.55569.706339639.57368.602689709.61567.231239749.63968.35941
9759.64565.920599829.68766.396699849.69963.003989879.71763.161739911.79558.38361
9935.44257.320549965.08553.032439976.12149.3590410006.3847.4234110020.2649.02843
10030.0354.6359610042.3363.2164110051.7367.2670710094.3369.68992 10135.470.44375
10155.9480.6759910176.4887.6638710197.0187.3116810248.3689.5753210252.2988.83993
#Mann= 3 , 0 , 0
9406.437  0.0496       09406.437  0.0496       010252.29  0.0496       0
#XS Ineff= 2 , 0
       09659.502                       0
Bank Sta=9406.437,10252.29
Exp/Cntr=0.3,0.1

Type RM Length L Ch R = 1 ,15720.69,275.109300,275.109300,275.109300
XS GIS Cut Line= 3
417399.279197872792383.149675876417412.300031155792851.899675891
417533.827808946793164.399675876
#Sta/Elev= 30
9726.878130.70789768.745130.2268 9808.76127.56829818.764125.96789858.779107.5176
9878.787101.73089888.79197.575219908.79983.815969918.80378.112699928.80673.47873
 9938.8170.791599948.81464.960959958.81861.612619978.826 50.84129998.83346.25686
10028.8551.4157710048.8556.6470510058.8657.9133710199.1461.7588810317.1667.70796
10327.8971.3181610338.6272.5987610381.5482.9502110392.2788.50105   1040392.46315
10423.9893.8777910456.6593.82974 10478.195.5893510488.8395.3800810531.11100.1984
#Mann= 3 , 0 , 0
9726.878  0.0456       09726.878  0.0456       010531.11  0.0456       0
#XS Ineff= 2 , 0
       0                               0
Bank Sta=9726.878,10531.11
Exp/Cntr=0.3,0.1

Type RM Length L Ch R = 1 ,15445.58,103.518100,103.518100,103.518100
XS GIS Cut Line= 3
417073.758364499792695.649675891417269.070864499792882.281620339
417475.234058976793092.785092562
#Sta/Elev= 30
9837.056114.31689852.605106.1644 9879.5490.192879894.09980.768659922.96563.88015
9935.59458.339419937.43957.890269949.42558.605889951.914 58.25679963.25753.99872
9977.08846.218729980.86445.6552410009.8145.1583310018.5845.2155310024.2946.43654
10038.7655.1172110046.2557.7778410053.2458.7961410101.57 60.373610158.5563.88962
 10244.365.4922510292.9767.2927110301.4769.2666910315.7681.8501210320.9684.96794
10330.0589.2894810348.9691.6796710362.9592.2625710390.9592.1275210401.8593.26798
#Mann= 3 , 0 , 0
9837.056   0.056       09837.056   0.056       010401.85   0.056       0
#XS Ineff= 2 , 0
       0                               0
Bank Sta=9837.056,10401.85
Exp/Cntr=0.3,0.1

Type RM Length L Ch R = 1 ,15342.06,229.609300,229.609300,229.609300
XS GIS Cut Line= 4
417035.466263801792688.115677044417056.299597144792839.157343701
417191.716263801 792934.64345482417285.466263801793297.490677029
#Sta/Elev= 30
9759.602 119.4079796.83692.600249806.931 84.41339817.02580.549499837.21566.63294
9847.30962.863299867.49959.892729877.59359.558479887.68857.694739907.87755.48814
9934.95655.589789956.919 53.34589959.42852.540839971.66445.612799991.62444.83004
10008.9845.2707110032.84 51.120310045.0856.6251610057.3260.9398610088.47  64.188
10181.42 66.223210212.4165.5110410346.6868.5031110357.0169.4791110377.6680.23637
10408.65 81.161410418.9887.66591 10429.393.1426510439.6397.4668710452.53104.4369
#Mann= 3 , 0 , 0
9759.602  0.0493       09759.602  0.0493       010452.53  0.0493       0
#XS Ineff= 2 , 0
       0                               0
Bank Sta=9759.602,10452.53
Exp/Cntr=0.3,0.1