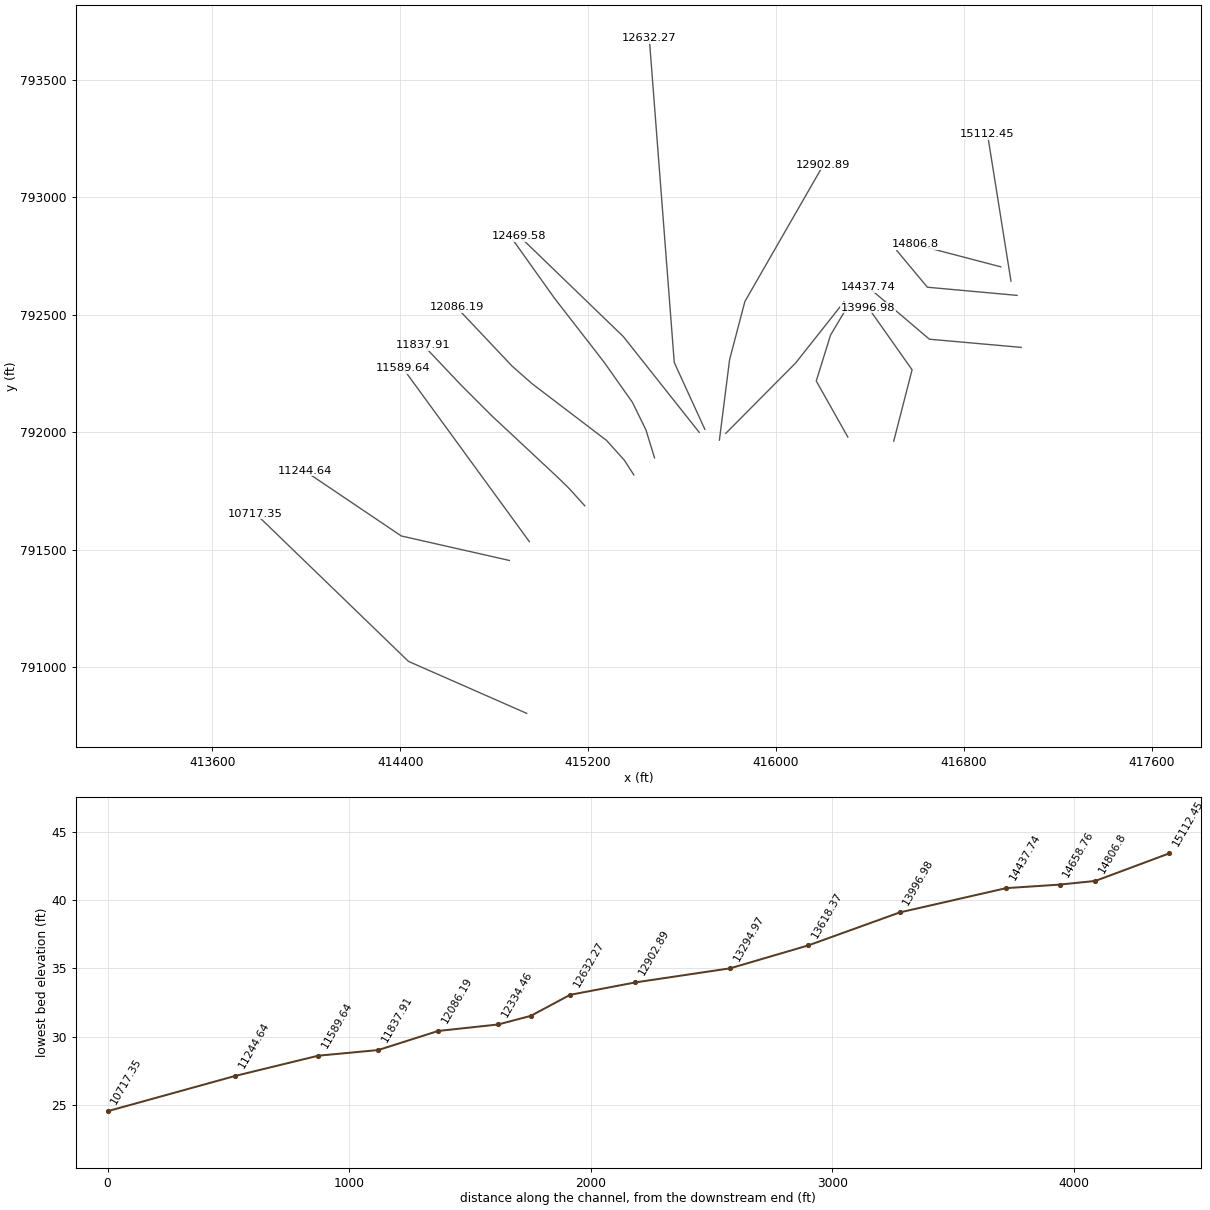
HEC-RAS study 4217_ras.prj: 4217

--- 4217_ras.g01 (geometry) --- (continued)

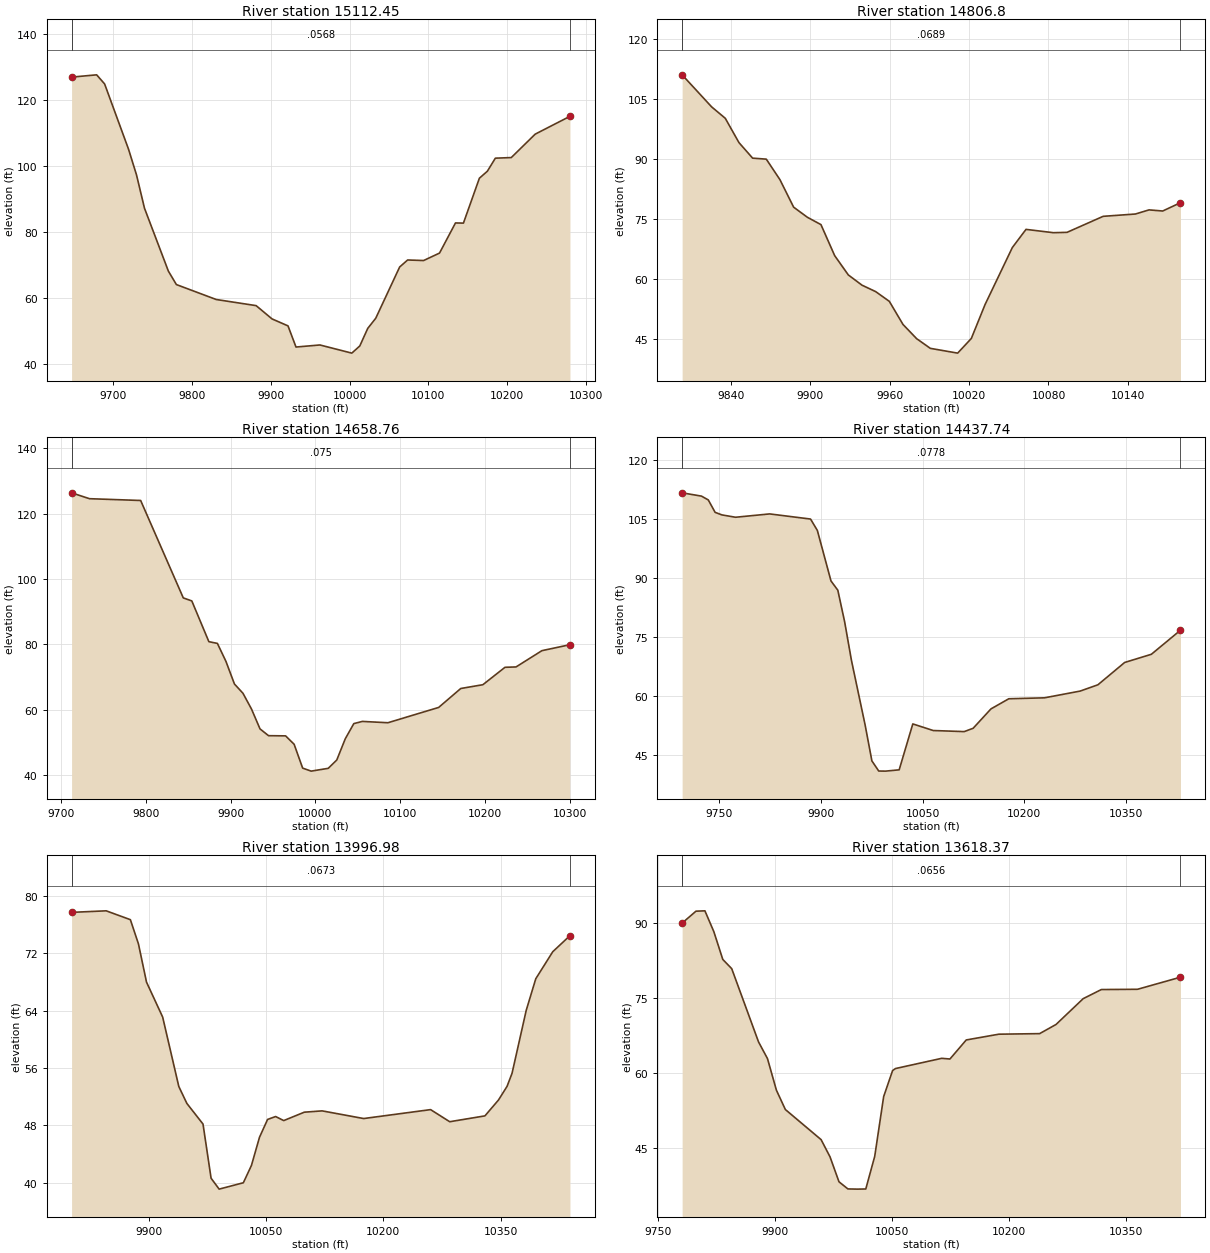
Type RM Length L Ch R = 1 ,15112.45,305.649200,305.649200,305.649200
XS GIS Cut Line= 2
 416999.97364226792643.566342562416900.147253394793268.566342548
#Sta/Elev= 30
9646.922126.83179678.754 127.527 9688.88 124.7749719.261105.03899729.38797.27596
9739.51487.208459769.89468.181139780.02164.137619830.65559.620869881.28957.77342
9901.54253.750669921.79651.649219931.92345.258479962.303 45.881810002.8143.41693
10012.9445.5815810023.0650.8991810033.1953.9509310063.5769.44709 10073.771.56669
10093.9571.40179 10114.273.6549410134.4682.7588210144.5882.7147110164.8496.28577
10174.9698.3912910185.09102.336110205.34102.521210235.73109.604310279.84114.9869
#Mann= 3 , 0 , 0
9646.922  0.0568       09646.922  0.0568       010279.84  0.0568       0
#XS Ineff= 2 , 0
       0                               0
Bank Sta=9646.922,10279.84
Exp/Cntr=0.3,0.1

Type RM Length L Ch R = 1 , 14806.8,148.048100,148.048100,148.048100
XS GIS Cut Line= 2
416956.570864499792704.330231443416591.987531155792799.816342562
#Sta/Elev= 30
9802.944111.08199825.243103.0623 9835.58100.19689845.91794.112129856.25590.22038
9866.59289.971089876.92984.825379887.26777.949159897.60475.431919907.94173.57516
9918.27865.826859928.61660.982089938.95358.42053 9949.29 56.80969959.62754.36949
9969.96548.586259980.30245.018099990.63942.5998310011.3141.4037910021.6545.07732
10031.9953.5343210052.6667.83669   1006372.3871710083.6771.5577310094.0171.64282
10121.3475.65493 10145.776.2317210156.0477.2662210166.3776.9851310179.8279.06859
#Mann= 3 , 0 , 0
9802.944  0.0689       09802.944  0.0689       010179.82  0.0689       0
#XS Ineff= 2 , 0
       0                               0
Bank Sta=9802.944,10179.82
Exp/Cntr=0.3,0.1

Type RM Length L Ch R = 1 ,14658.76,221.016700,221.016700,221.016700
XS GIS Cut Line= 3
417026.015308946792582.802453652416644.070864528792617.524675891
416513.862531155792773.774675891
#Sta/Elev= 30
9712.829126.34189733.931124.54539794.178123.99599844.38594.171259854.42693.24242
9874.50880.76708 9884.5580.240539894.59174.751629904.63267.808119914.67364.96393
9924.71460.141419934.75654.053989944.79751.986379964.87951.926989974.92149.35387
9984.96242.051639995.00341.1336110015.0941.9906110025.1344.5354810035.1751.04472
10045.2155.6826910055.2556.3531610085.3755.9499710145.1360.6339310171.16 66.4306
 10197.267.5935310223.23 72.919610236.2573.0343810266.7278.0156710299.7479.84463
#Mann= 3 , 0 , 0
9712.829   0.075       09712.829   0.075       010299.74   0.075       0
#XS Ineff= 2 , 0
       0                               0
Bank Sta=9712.829,10299.74
Exp/Cntr=0.3,0.1

Type RM Length L Ch R = 1 ,14437.74,440.756800,440.756800,440.756800
XS GIS Cut Line= 3
417043.376420051792361.448286995416652.751420051792396.170509204
416392.334753394792617.524675891
#Sta/Elev= 30
9696.005111.73879724.493110.89989734.533109.93149744.572106.77049754.611106.1167
 9774.69105.51919824.887106.36879885.124105.06219895.163102.15859915.242 89.2944
9925.28286.949899935.32178.921789945.36169.082729965.43952.681619975.47943.48339
9985.518 40.90459995.55840.8773610015.6441.2056510035.72 52.897810065.8351.21433
10111.4750.9399810124.5951.7884110150.8456.7224910177.0959.3022310229.5959.54196
10282.0861.2538110308.3362.8605610347.7168.5439110387.0870.6306510429.9576.76263
#Mann= 3 , 0 , 0
9696.005  0.0778       09696.005  0.0778       010429.95  0.0778       0
#XS Ineff= 2 , 0
       0                               0
Bank Sta=9696.005,10429.95
Exp/Cntr=0.3,0.1

Type RM Length L Ch R = 1 ,13996.98,378.610800,378.610800,378.610800
XS GIS Cut Line= 3
416500.841697842791962.142731428416578.966697842792265.962175876
416392.334753394792530.719120324
#Sta/Elev= 30
9801.10777.734729845.35977.949639876.33576.71555 9886.6673.334679896.986 67.9955
9917.63663.120949938.28753.430519948.61251.061999969.263 48.18379979.58840.62316
9989.91339.0993410020.8939.9887110031.2142.4014810041.5446.3387110051.8748.82663
10062.1949.2341410072.5248.6671410098.8849.84044 10121.750.0230710174.8148.95282
10260.4550.1986510284.9248.5081210329.9749.3255210347.3351.5432310358.3353.45856
10364.6855.27871 10382.864.0610910395.0368.4698910416.75 72.239610438.7474.48509
#Mann= 3 , 0 , 0
9801.107  0.0673       09801.107  0.0673       010438.74  0.0673       0
#XS Ineff= 2 , 0
       0                               0
Bank Sta=9801.107,10438.74
Exp/Cntr=0.3,0.1

Type RM Length L Ch R = 1 ,13618.37,323.399800,323.399800,323.399800
XS GIS Cut Line= 4
416305.529197872791979.503842548416170.980586708792218.219120324
416231.744475603792413.531620324416314.209753394792552.420509204
#Sta/Elev= 30
9780.49790.062019798.28592.452849809.76492.524339821.24388.339629832.72282.77167
9844.20180.918629878.63966.221959890.11862.879729901.59756.535849913.07652.65842
9958.99246.616479970.47143.16222 9981.9538.160219993.42936.72639 10005.636.68661
10016.3936.7153710027.8743.2724310039.3555.2551310050.8260.4766310054.5260.87868
10113.9862.9332710124.4662.79071 10145.466.6149210187.2967.7723410239.66 67.8842
10260.7769.7272510295.6674.9078910318.9276.7296410365.4476.7824710420.59 79.2099
#Mann= 3 , 0 , 0
9780.497  0.0656       09780.497  0.0656       010420.59  0.0656       0
#XS Ineff= 2 , 0
       0                               0
Bank Sta=9780.497,10420.59
Exp/Cntr=0.3,0.1

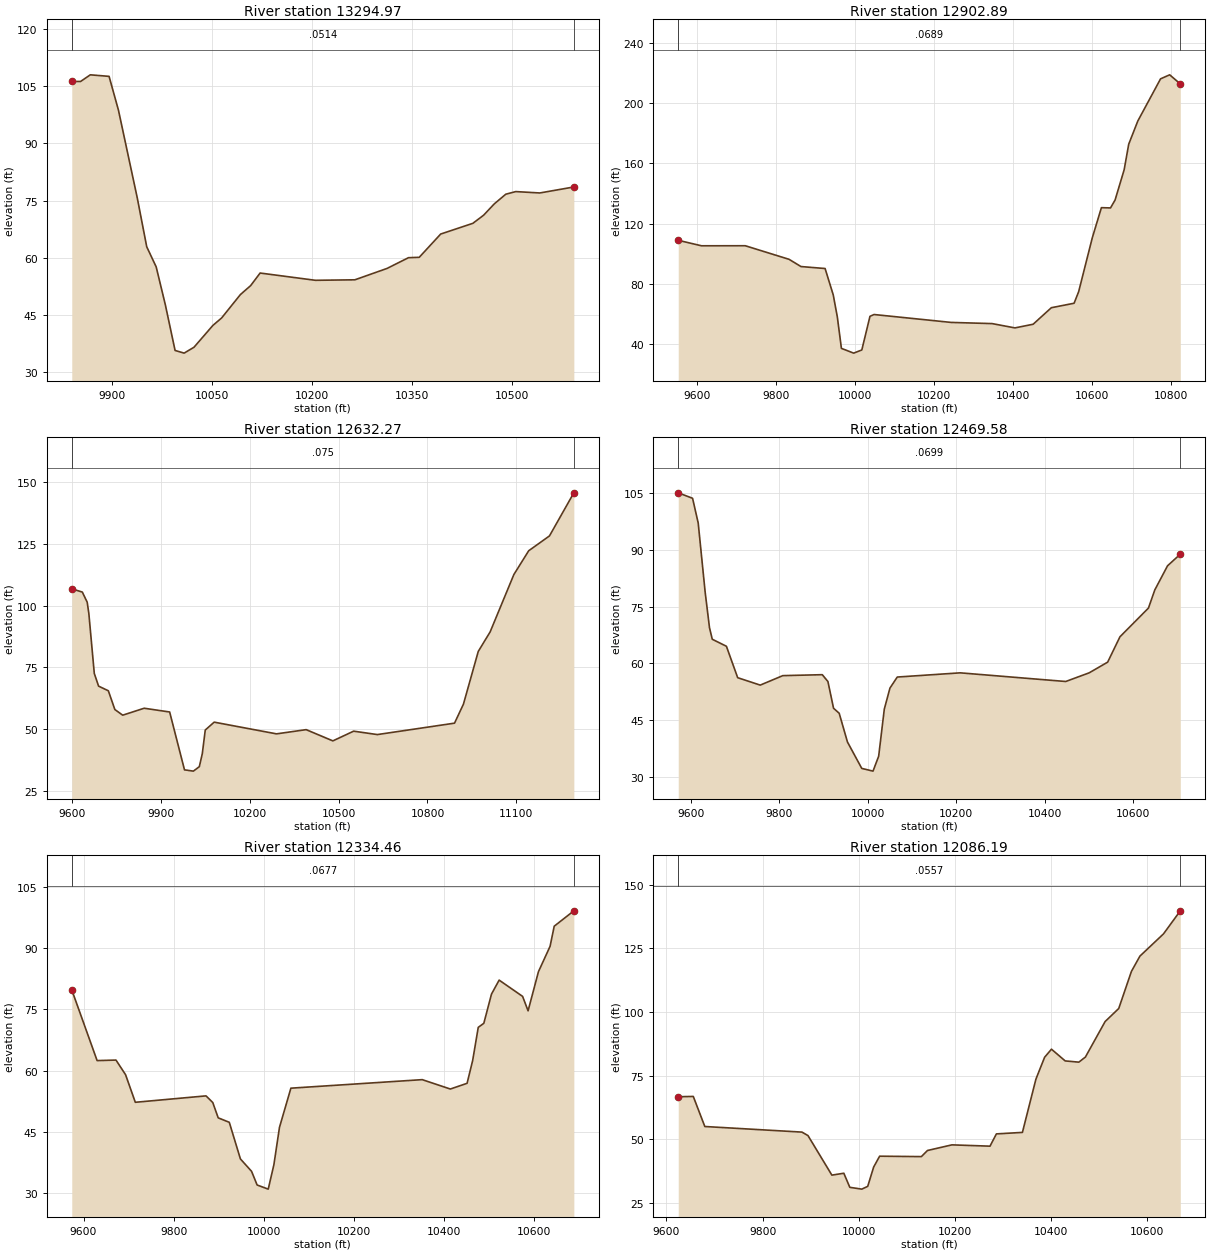
Type RM Length L Ch R = 1 ,13294.97,392.077000,392.077000,392.077000
XS GIS Cut Line= 3
415785.673681796791995.234637991416082.982709587792294.713804677
416289.145904034792555.130471334
#Sta/Elev= 30
9839.345106.21659852.583106.21229867.197107.95479895.379107.5517 9909.4798.69145
9937.65275.76797 9951.9462.895189966.13457.619549979.925 47.66489994.52135.71536
10008.1135.0113710022.91 36.5486 10051.342.2705710064.4744.2357310092.6550.36071
10108.0752.7141610122.2756.0023310205.3854.0974110264.5954.2289110312.9257.21053
10345.1460.0248510361.26 60.123110393.4866.2219510441.8169.0328510457.9271.15661
10474.0374.1354710491.2876.6636710506.25 77.3511 10542.376.9879310593.4978.55859
#Mann= 3 , 0 , 0
9839.345  0.0514       09839.345  0.0514       010593.49  0.0514       0
#XS Ineff= 2 , 0
       0                10355.93       0
Bank Sta=9839.345,10593.49
Exp/Cntr=0.3,0.1

Type RM Length L Ch R = 1 ,12902.89,270.619100,270.619100,270.619100
XS GIS Cut Line= 4
415758.654197842791966.483009219415802.056975603792309.364953667
 415867.16114226792556.760786995416201.362531155793138.358009219
#Sta/Elev= 30
9551.712108.84529610.696105.21319721.574105.24379832.45196.242319862.69191.43402
9923.838 90.12359944.51972.615769954.85957.97271  9965.2 37.13919996.22133.98093
 10016.936.0759110037.5858.4116910047.9259.5991210243.3954.3592810347.1953.57641
10404.8550.7184510450.9953.1497410497.1264.1126110554.7967.0850510566.3274.71642
10600.92110.528510623.99130.503110647.05130.336310658.59135.547310681.65155.6765
10693.19172.618310716.26188.029310773.92216.009510796.99218.664910823.93 212.653
#Mann= 3 , 0 , 0
9551.712  0.0689       09551.712  0.0689       010823.93  0.0689       0
#XS Ineff= 2 , 0
       0                10094.69       0
Bank Sta=9551.712,10823.93
Exp/Cntr=0.3,0.1

Type RM Length L Ch R = 1 ,12632.27,162.692700,162.692700,162.692700
XS GIS Cut Line= 3
415696.697987378 792012.59574911415566.489654034792296.883943543
415460.152848482793677.092276871
#Sta/Elev= 30
9597.681106.79919633.323105.51069649.788101.41069655.32196.935039673.802 72.5887
9688.31867.455239721.31565.571169743.31357.98846 9769.8655.701089842.30458.51031
9928.53956.990619978.68833.5910310008.7833.0710310028.84 34.875810038.8740.12959
 10048.949.6970710078.9852.8820810289.6148.14641 10389.949.8475710480.1745.30801
10550.38 49.234110630.6147.8563910891.3852.4734310921.4760.1476810971.6281.49629
11011.7489.3845711091.98 112.59611142.13122.217311212.33128.222711294.67145.6473
#Mann= 3 , 0 , 0
9597.681   0.075       09597.681   0.075       011294.67   0.075       0
#XS Ineff= 2 , 0
       09877.115        10127.29       0
Bank Sta=9597.681,11294.67
Exp/Cntr=0.3,0.1

Type RM Length L Ch R = 1 ,12469.58,135.122200,135.122200,135.122200
XS GIS Cut Line= 3
415672.826459587791999.574915767415349.475765139792407.561026886
414906.767431825792835.078388005
#Sta/Elev= 30
9570.897105.07519603.339103.63359616.09997.088789631.79678.849629641.61869.44705
9647.89666.381639679.89864.527329705.418 56.21969756.45754.263389807.49656.76579
9896.81657.015479909.57555.209759922.33548.145329935.09546.82168 9953.7939.23157
9986.13532.2529310011.65 31.531610024.4135.4745310037.1747.9185610049.9353.47128
10066.4956.3938710208.9257.5041810447.6855.2173410500.8557.5133510542.5660.33478
10570.3667.0316810634.8374.6188810649.2279.4147110678.0185.7867610706.92  88.868
#Mann= 3 , 0 , 0
9570.897  0.0699       09570.897  0.0699       010706.92  0.0699       0
#XS Ineff= 2 , 0
       09850.258        10107.25       0
Bank Sta=9570.897,10706.92
Exp/Cntr=0.3,0.1

Type RM Length L Ch R = 1 ,12334.46,248.273000,248.273000,248.273000
XS GIS Cut Line= 6
415482.571382968791890.908791692415445.754363626792010.533478933
415388.239330961792127.608467991415266.483162057792300.040847142
415057.749979053 792568.86338902414880.144167126792818.293998707
#Sta/Elev= 30
9573.89479.817599630.09362.450919672.00162.577689693.24258.984439714.84352.21677
9871.68553.791249886.64952.15327 9898.6648.399189923.23547.306349947.94738.31052
 9972.66   35.279985.01631.9118910009.6330.9028610022.1836.89944 10034.646.08129
10059.8955.6818410351.2357.7741810413.5555.4726310450.6656.8768310463.0462.48146
10475.41 70.6039 10487.871.6096510504.7878.7757910521.77 82.203910573.7778.21112
10585.9674.6741510608.9184.2654710634.6990.4936810643.9295.4390110687.4399.21244
#Mann= 3 , 0 , 0
9573.894  0.0677       09573.894  0.0677       010687.43  0.0677       0
#XS Ineff= 2 , 0
       09851.184        10110.93       0
Bank Sta=9573.894,10687.43
Exp/Cntr=0.3,0.1

Type RM Length L Ch R = 1 ,12086.19,248.273000,248.273000,248.273000
XS GIS Cut Line= 6
 415394.31286211791818.447363476 415353.94605329791881.069712824
415278.000059711791965.442186916414961.760986646792206.227747704
414875.850534815 792281.89401189414640.112609178792531.465365296
#Sta/Elev= 30
9624.62466.723659655.91966.831479679.89355.021369881.85952.823769894.351 51.4609
9944.03335.924849968.87436.668529981.29531.1333810006.1330.4287610018.5131.50774
10030.8939.1028610043.2743.3611210130.0943.2006510142.7945.6018110193.5947.81269
10272.7147.3015610286.04 52.117410340.1252.7083910368.2173.6387910386.2782.21896
10400.5285.39396   10429 80.788710457.4380.2994410471.0982.3061710512.07 96.2458
10540.38101.374610566.72115.934810584.41121.946810633.39130.676610668.36139.7334
#Mann= 3 , 0 , 0
9624.624  0.0557       09624.624  0.0557       010668.36  0.0557       0
#XS Ineff= 2 , 0
       09862.847        10122.63       0
Bank Sta=9624.624,10668.36
Exp/Cntr=0.3,0.1

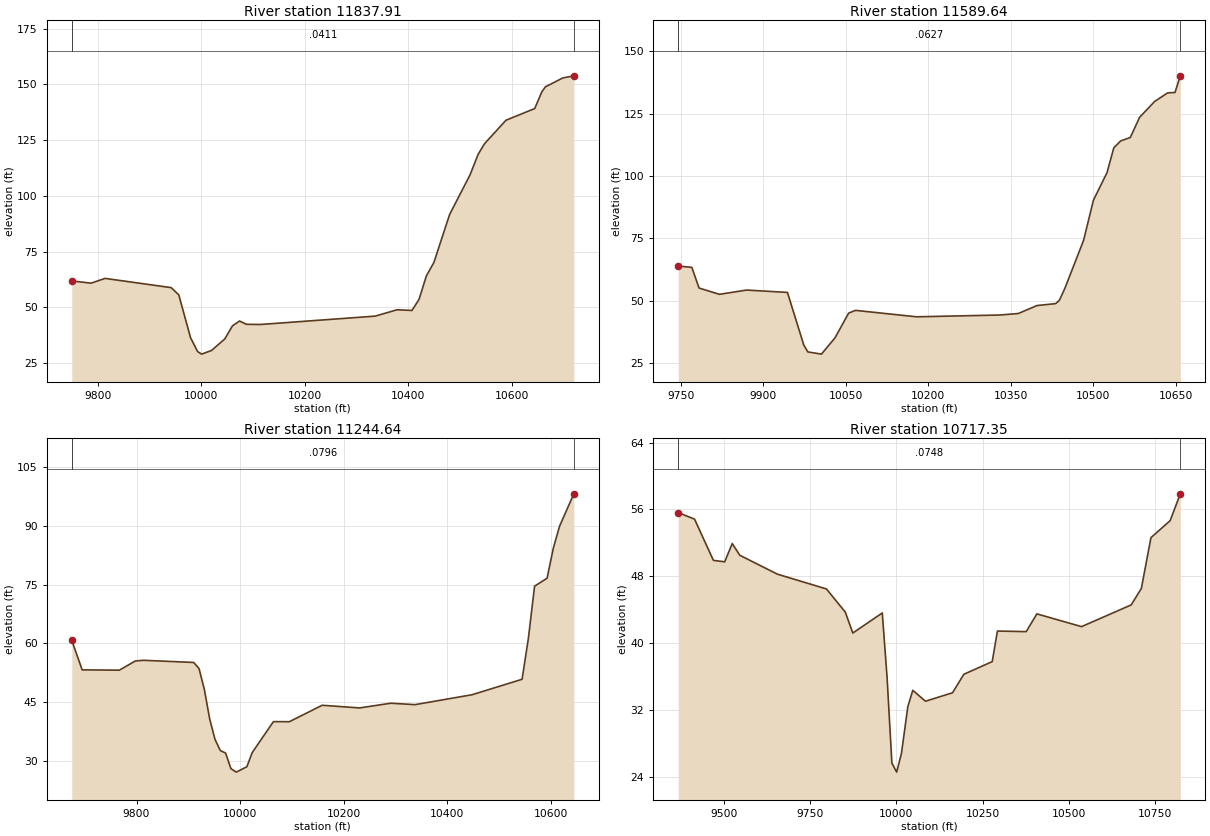
Type RM Length L Ch R = 1 ,11837.91,248.273000,248.273000,248.273000
XS GIS Cut Line= 6
415185.649947014791686.766883082415120.519862733791758.957095074
415073.341041115791805.431859593414790.528733339792069.262583715
414663.141559688792196.536355418414497.972465604792370.711631475
#Sta/Elev= 30
9749.68761.855319786.98760.85172 9814.0662.98114 9941.8658.848049956.52555.60415
9979.25136.409849992.92230.1806310000.7129.0318410019.8830.6847410045.32 35.8092
10060.4441.7576710073.9543.8656410087.4742.3993110114.5142.3255910336.0546.06553
10378.4648.9210510407.1248.6098810420.8753.5548910435.0164.0884910449.5770.10901
10480.0491.6672910519.54 109.44110535.05118.6014 10547.3123.324710588.94133.9029
10644.45139.1404 10658.2146.604910665.17148.884510698.82152.865310720.09153.8117
#Mann= 3 , 0 , 0
9749.687  0.0411       09749.687  0.0411       010720.09  0.0411       0
#XS Ineff= 2 , 0
       0                10340.09       0
Bank Sta=9749.687,10720.09
Exp/Cntr=0.3,0.1

Type RM Length L Ch R = 1 ,11589.64,345.005600,345.005600,345.005600
XS GIS Cut Line= 2
414949.561823256791534.390615402414411.386846856792272.787419784
#Sta/Elev= 30
 9744.9963.898539769.71363.375129782.86755.099089819.98952.572559869.48654.28429
9943.73153.335669973.44832.280699980.85429.50581 10005.628.6186910030.3535.16322
 10055.145.0410810067.4746.1496410178.8443.5684610329.9844.2841910363.9444.88806
 10397.948.0813410431.8548.85055 10438.750.2079110448.8355.0765210482.7874.26451
10500.5790.2641110525.32101.313610537.69 111.27410550.07114.008310567.67115.4067
10584.65123.476910611.94129.819810635.59133.262710649.06133.4359 10658.7140.0991
#Mann= 3 , 0 , 0
 9744.99  0.0627       0 9744.99  0.0627       0 10658.7  0.0627       0
#XS Ineff= 2 , 0
       0                10393.15       0
Bank Sta=9744.99,10658.7
Exp/Cntr=0.3,0.1

Type RM Length L Ch R = 1 ,11244.64,527.288200,527.288200,527.288200
XS GIS Cut Line= 3
414864.556975633791454.330231443414404.487531155  791558.4968981
 413992.16114229791836.274675891
#Sta/Elev= 30
9675.06960.755299695.12153.234699766.89353.152479797.65255.500949813.95655.67525
9910.43655.119939920.68953.545999930.94348.222669941.19640.723389951.44935.50368
9961.70232.644459971.95531.992429982.20828.023529992.46127.1326110012.9728.50169
10023.2232.1111710064.2340.0204310094.9940.0015710158.2244.1983910230.5743.52117
10290.8644.72319 10337.444.35423 10447.646.8866910544.07 50.830110556.1261.17407
10568.1874.59902 10592.376.6299710604.3584.2825210616.4189.9027410643.95 98.1638
#Mann= 3 , 0 , 0
9675.069  0.0796       09675.069  0.0796       010643.95  0.0796       0
#XS Ineff= 2 , 0
       0                10506.58       0
Bank Sta=9675.069,10643.95
Exp/Cntr=0.3,0.1

Type RM Length L Ch R = 1 ,10717.35,927.314600,927.314600,927.314600
XS GIS Cut Line= 3
414938.341697872790803.288564786414434.869475603791024.642731428
413783.827808946791653.983009219
#Sta/Elev= 30
9367.68255.614999415.02754.829699469.64649.896519502.41849.725399524.26551.91232
9546.11350.507789655.35148.243619797.36146.47633 9851.9843.701739873.82741.20176
9959.20943.606459973.11735.889579987.02625.6408810000.9324.5560810014.8426.81571
10033.2832.3962610047.6734.3454910084.3833.0414610162.7834.0536110195.6536.26592
10277.8837.7796110293.0141.4393310376.4641.3700410407.3743.4932610536.8641.96727
10680.7444.5664810710.2646.5398810738.0852.6181910793.7154.6497910823.16 57.8608
#Mann= 3 , 0 , 0
9367.682  0.0748       09367.682  0.0748       010823.16  0.0748       0
#XS Ineff= 2 , 0
       09808.213        10497.21       0
Bank Sta=9367.682,10823.16
Exp/Cntr=0.3,0.1