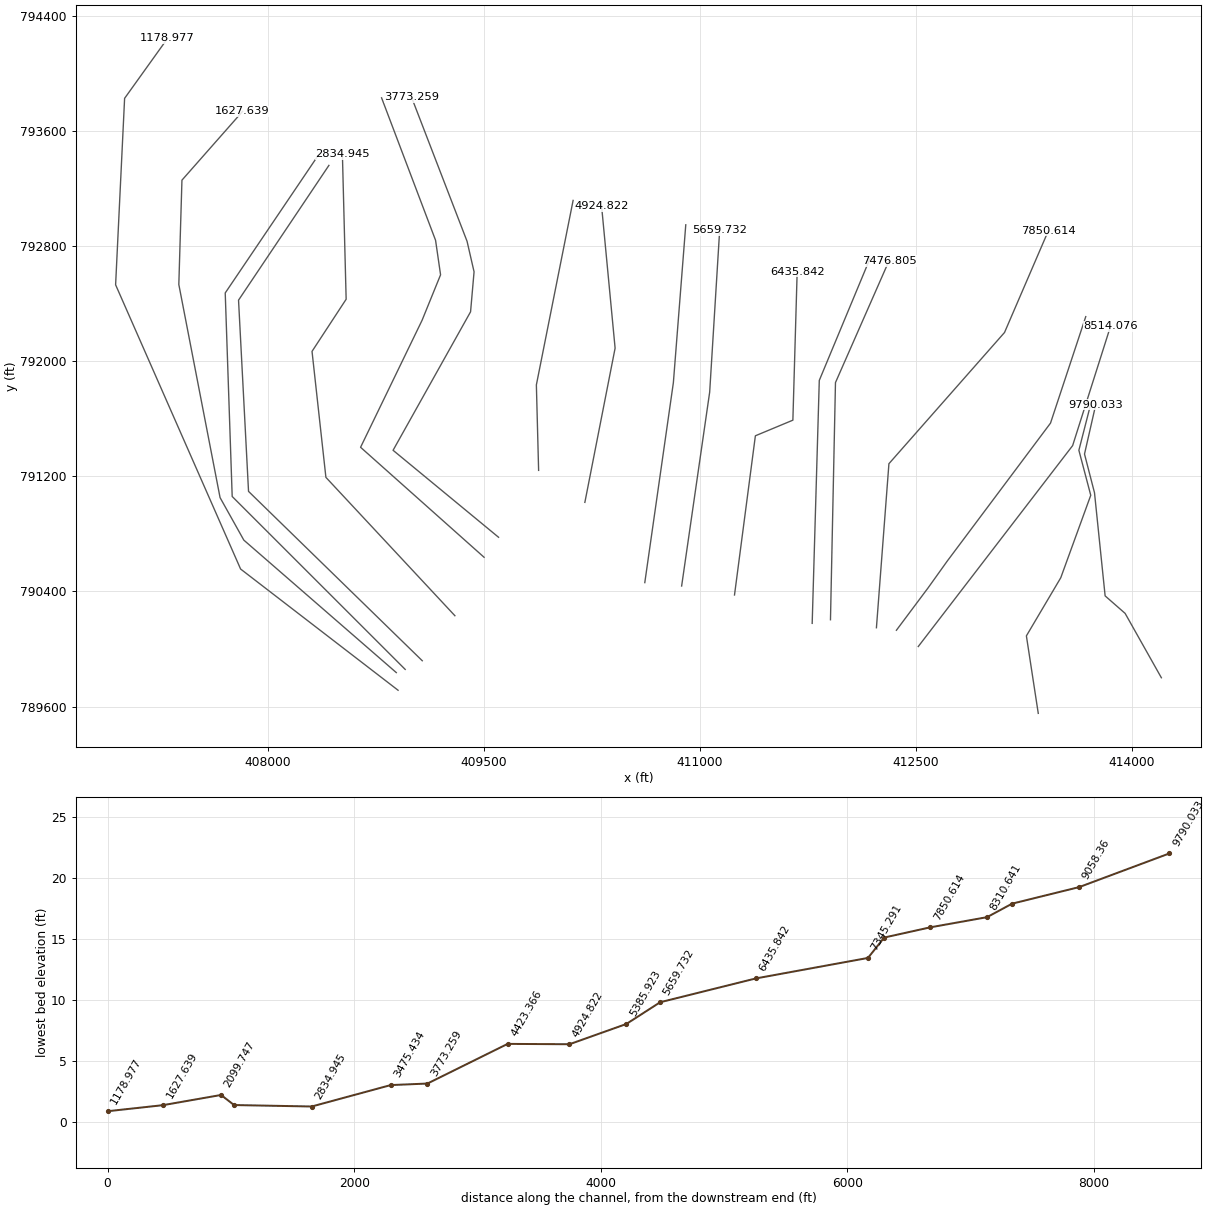
HEC-RAS study 4217_ras.prj: 4217

--- 4217_ras.g01 (geometry) --- (continued)

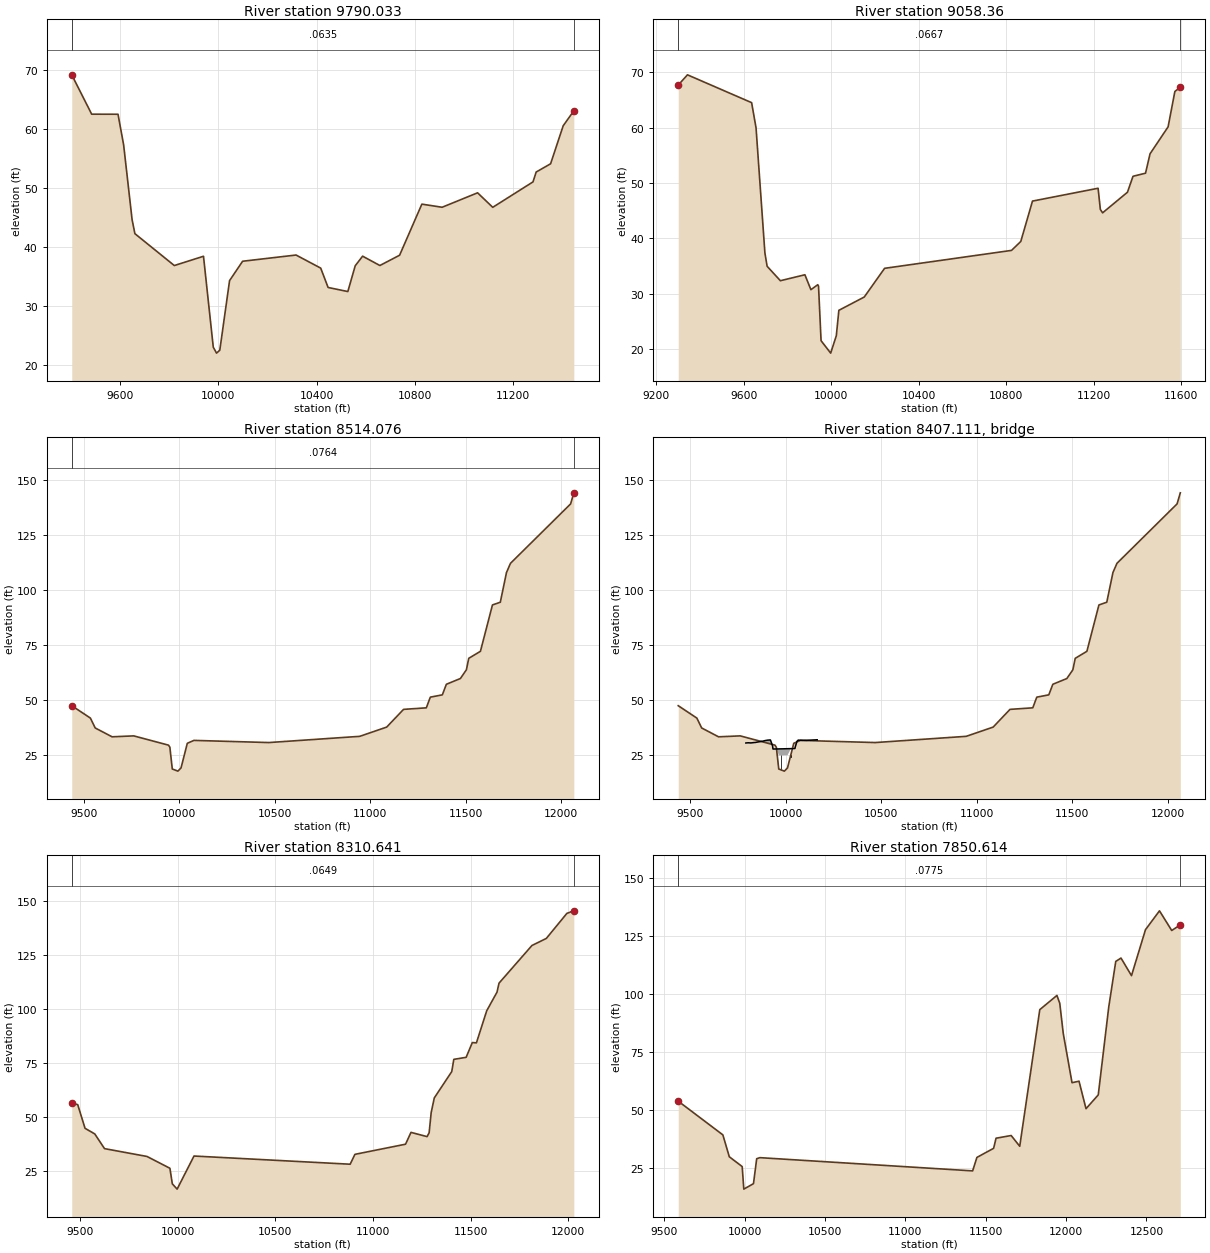
Type RM Length L Ch R = 1 ,9790.033,731.672400,731.672400,731.672400
XS GIS Cut Line= 6
414204.834753394789800.684398115 413953.09864226790247.733009204
413814.209753394 790369.26078698413740.425031155791085.406620324
413670.980586708791354.503842562413749.105586708 791697.38578698
#Sta/Elev= 30
9401.981 69.10979483.16762.452599590.557 62.4404 9613.5157.25358 9647.9444.61515
9659.41642.238329820.08636.847249939.08338.416169978.94723.040399992.234   22.03
10005.5222.5219610045.3834.2948910098.54 37.573510316.4738.62539   1041736.41143
10447.1633.1363410527.5832.4495310557.7436.81254 10587.938.4295710658.2736.85132
10738.69 38.593410829.4347.2341610912.0546.7058711056.6449.1500811118.4646.69496
11282.56 50.997411295.5852.6683111354.3554.0629211405.6360.4864811449.11 63.0243
#Mann= 3 , 0 , 0
9401.981  0.0635       09401.981  0.0635       011449.11  0.0635       0
#XS Ineff= 2 , 0
       0                               0
Bank Sta=9401.981,11449.11
Exp/Cntr=0.3,0.1

Type RM Length L Ch R = 1 , 9058.36,544.284300,544.284300,544.284300
XS GIS Cut Line= 6
413349.800031185789553.288564771413267.334753394790091.483009204
413506.050031185790495.128842562413714.383364499791068.045509204
413631.918086708791380.545509204 413718.72364226791719.087175891
#Sta/Elev= 30
9299.76467.689879341.96269.541149635.34764.51338 9655.5859.961029696.04737.37533
9706.16434.957759766.86432.347069878.94333.421879906.415 30.72679937.87731.62882
9941.26931.374199952.88721.512039996.81119.2667410022.5922.4149710034.2126.99903
10150.3929.4042710243.3334.58566 10823.837.8257510866.0939.4407910919.5746.73102
11219.5949.0504511229.93 45.220211240.2744.6136111353.8448.33239 11379.251.21528
11436.4351.7689811457.0855.2729411539.6660.1397311570.6466.53423 11595.567.29376
#Mann= 3 , 0 , 0
9299.764  0.0667       09299.764  0.0667       0 11595.5  0.0667       0
#XS Ineff= 2 , 0
       0                               0
Bank Sta=9299.764,11595.5
Exp/Cntr=0.3,0.1

Type RM Length L Ch R = 1 ,8514.076,203.435000,203.435000,203.435000
XS GIS Cut Line= 3
412516.466697842790017.698286995413588.512770772791412.978579566
413851.533604085792241.103579551
#Sta/Elev= 30
9437.58347.595779535.06741.975479560.28937.492039648.56533.480499762.063 33.8996
9943.98529.699599951.22628.723029963.837 18.87499993.22417.9067210009.6419.37014
10042.4630.5344810077.3331.8519410469.2130.8713810945.1933.69313 11086.237.88686
11174.4845.92907 11293.746.6311411314.69 51.476711377.6452.5190311398.6357.31366
11472.0759.9261111503.55 63.9049 11515.969.09213   1157772.2776111639.9593.31482
11681.0794.54729 11713.4 108.02311734.38 112.20112049.15139.169512066.04 144.188
#Mann= 3 , 0 , 0
9437.583  0.0764       09437.583  0.0764       012066.04  0.0764       0
#XS Ineff= 2 , 0
       0                               0
Bank Sta=9437.583,12066.04
Exp/Cntr=0.3,0.1

Type RM Length L Ch R = 3 ,8407.111,,,
BEGIN DESCRIPTION:
END DESCRIPTION:
Bridge Culvert--1,0,-1,-1, 0
Deck Dist Width WeirC Skew NumUp NumDn MinLoCord MaxHiCord MaxSubmerge Is_Ogee
82.196550,39.041900,2.6,0, 47, 47, , , 0.95, 0, 0,0,,
 9791.68 9792.74 9805.08 9805.94 9817.42 9823.01 9829.76 9834.48 9839.77 9842.34
 9855.08 9855.91 9867.82 9872.06 9880.56 9888.20 9893.30 9904.34 9906.04 9918.78
 9920.48 9927.33 9927.33 9931.52 9933.5710048.3710049.6110058.9110065.7510071.65
10072.6710072.6710081.9010084.3910097.1310098.0410109.8710114.1810122.6010130.32
10135.3410146.4610148.0810159.3310160.8010162.6910165.02
   30.67   30.69   30.78   30.76   30.70   30.75   30.83   30.86   30.90   30.93
   31.14   31.15   31.31   31.40   31.51   31.69   31.79   31.96   31.96   32.07
   32.02   30.33   30.33   29.29   27.93   28.16   28.66   31.41   32.00   31.93
   31.93   31.93   31.91   31.89   31.89   31.89   31.88   31.90   31.94   31.97
   31.99   32.06   32.06   32.11   32.13   32.14   32.14
 -969.33 -969.31 -969.22 -969.24 -969.30 -969.25 -969.17 -969.14 -969.10 -969.07
 -968.86 -968.85 -968.69 -968.60 -968.49 -968.31 -968.21 -968.04 -968.04 -967.93
 -967.98 -969.67   27.33   26.29   24.93   25.16   25.66   28.41   29.00   28.93
   28.93 -968.07 -968.09 -968.11 -968.11 -968.11 -968.12 -968.10 -968.06 -968.03
 -968.01 -967.94 -967.94 -967.89 -967.87 -967.86 -967.86
 9791.68 9792.74 9805.08 9805.94 9817.42 9823.01 9829.76 9834.48 9839.77 9842.34
 9855.08 9855.91 9867.82 9872.06 9880.56 9888.20 9893.30 9904.34 9906.04 9918.78
 9920.48 9927.33 9927.33 9931.52 9933.5710048.3710049.6110058.9110065.7510071.65
10072.6710072.6710081.9010084.3910097.1310098.0410109.8710114.1810122.6010130.32
10135.3410146.4610148.0810159.3310160.8010162.6910165.02
   30.67   30.69   30.78   30.76   30.70   30.75   30.83   30.86   30.90   30.93
   31.14   31.15   31.31   31.40   31.51   31.69   31.79   31.96   31.96   32.07
   32.02   30.33   30.33   29.29   27.93   28.16   28.66   31.41   32.00   31.93
   31.93   31.93   31.91   31.89   31.89   31.89   31.88   31.90   31.94   31.97
   31.99   32.06   32.06   32.11   32.13   32.14   32.14
 -969.33 -969.31 -969.22 -969.24 -969.30 -969.25 -969.17 -969.14 -969.10 -969.07
 -968.86 -968.85 -968.69 -968.60 -968.49 -968.31 -968.21 -968.04 -968.04 -967.93
 -967.98 -969.67   27.33   26.29   24.93   25.16   25.66   28.41   29.00   28.93
   28.93 -968.07 -968.09 -968.11 -968.11 -968.11 -968.12 -968.10 -968.06 -968.03
 -968.01 -967.94 -967.94 -967.89 -967.87 -967.86 -967.86
Pier Skew, UpSta & Num, DnSta & Num=  ,9975.28, 2 ,9975.28, 2 , 0 , 0 , 0 ,,
    3.00    3.00
 -971.99   28.01
    3.00    3.00
 -971.99   28.01
Pier Skew, UpSta & Num, DnSta & Num=  ,10024.72, 2 ,10024.72, 2 , 0 , 0 , 0 ,,
    3.00    3.00
 -971.89   28.11
    3.00    3.00
 -971.89   28.11
BR Coef=-1 , 0 , 0 ,, 0 ,,,0.8,0,1,0,
WSPro=,,,, 1 ,,,, 0 ,,,, 0 ,,,,-1 ,-1 ,-1 , 0 , 0 , 0 , 0 , 0
BC Design=,, 0 ,, 0 ,,,,,,

Type RM Length L Ch R = 1 ,8310.641,460.027400,460.027400,460.027400
XS GIS Cut Line= 5
412364.556975603790130.545509204412585.221033126790425.747482836
412717.512699813790610.816927254413434.866937399791569.228579566
413679.658604115792308.811912879
#Sta/Elev= 30
 9456.5456.511489487.07255.823249524.52744.898929574.46742.290249624.30435.50519
9841.91731.888579959.39626.429519971.68819.253559996.27216.79806 10082.832.08791
10882.8128.30412 10907.232.8633111166.5137.5462311194.4943.0110811276.8841.05138
11287.4142.8276911297.95 52.178111313.8158.9248711403.2871.0968211413.8276.74156
11477.0277.6796311508.6284.4900511529.6884.3639111582.3599.1736411635.02107.7631
11645.55111.942411814.09129.329311887.82132.595111993.16144.171412028.78 145.344
#Mann= 3 , 0 , 0
 9456.54  0.0649       0 9456.54  0.0649       012028.78  0.0649       0
#XS Ineff= 2 , 0
       0                               0
Bank Sta=9456.54,12028.78
Exp/Cntr=0.3,0.1

Type RM Length L Ch R = 1 ,7850.614,373.808200,373.808200,373.808200
XS GIS Cut Line= 4
412225.781289279790147.993047163412312.586844832 791287.31596382
413115.538233727792198.774297148413419.357678145792904.069436029
#Sta/Elev= 30
9585.65653.858029863.46639.339899903.58229.905469983.81425.678629993.84315.96527
10054.0218.3252410074.0729.0668110094.1329.52398 11418.2 23.827111444.85 29.6302
11548.8433.5459211563.9737.9030711658.0839.0611111711.3934.4336911836.2793.29543
11942.9899.4156111960.6496.0008911982.4282.9894112036.8661.8187712080.4262.46631
12123.97 50.616812200.1956.5670912265.5294.4504912309.07114.065612341.74 115.521
12407.07107.942812494.17127.742212581.28135.8646 12657.5127.390912710.93129.8133
#Mann= 3 , 0 , 0
9585.656  0.0775       09585.656  0.0775       012710.93  0.0775       0
#XS Ineff= 2 , 0
       0                               0
Bank Sta=9585.656,12710.93
Exp/Cntr=0.3,0.1

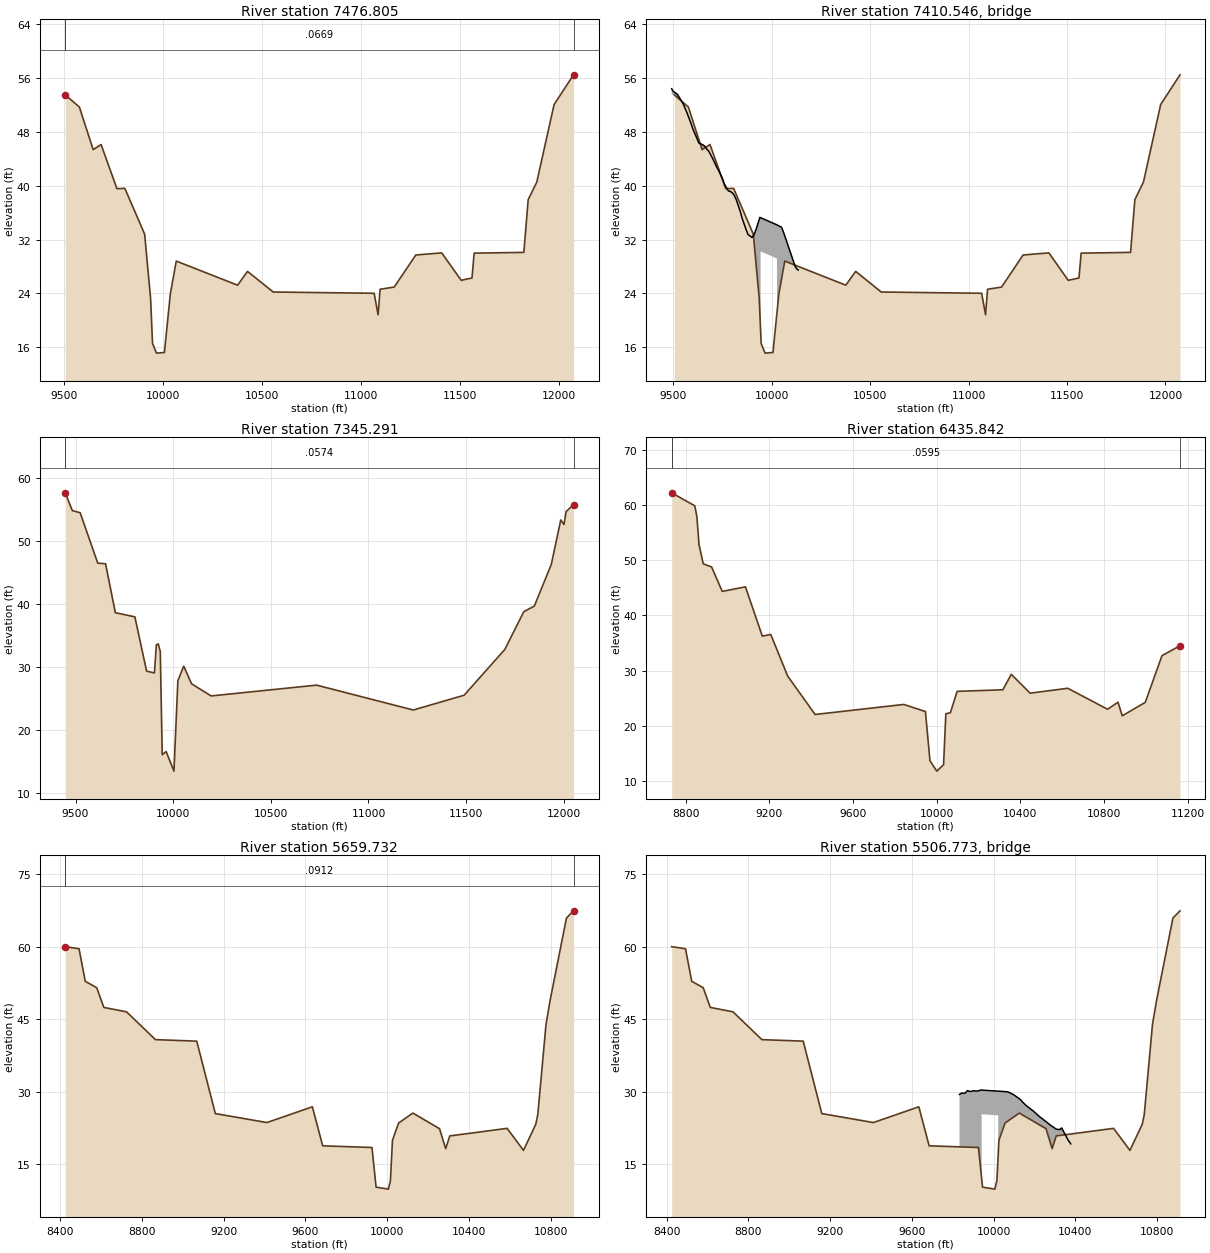
Type RM Length L Ch R = 1 ,7476.805,131.514500,131.514500,131.514500
XS GIS Cut Line= 3
411906.657670051790203.606851816 411941.37989226791850.742268488
 412312.47364226792694.926296264
#Sta/Elev= 30
9504.40153.47524 9575.8151.686379645.82545.345619685.83446.105229765.85239.54836
9805.86139.592989905.88332.80616 9935.8923.299589945.89216.560339965.89715.12671
10005.9115.2248310035.91 23.942510065.9228.7935810375.9925.21591   1042627.26744
10556.0324.2033511066.1424.0139511086.1520.8259511096.1524.6130611167.4824.93897
11276.7129.6977711407.7930.0147611506.1125.9388611560.7226.2886111571.6529.97377
11822.8930.0874611844.7437.9125211888.4340.5365311975.8252.0443612074.0556.45535
#Mann= 3 , 0 , 0
9504.401  0.0669       09504.401  0.0669       012074.05  0.0669       0
#XS Ineff= 2 , 0
       0                11602.29       0
Bank Sta=9504.401,12074.05
Exp/Cntr=0.3,0.1

Type RM Length L Ch R = 3 ,7410.546,,,
BEGIN DESCRIPTION:
END DESCRIPTION:
Bridge Culvert--1,0,-1,-1, 0
Deck Dist Width WeirC Skew NumUp NumDn MinLoCord MaxHiCord MaxSubmerge Is_Ogee
33.769100,63.976300,2.6,0, 40, 40, , , 0.95, 0, 0,0,,
 9491.17 9499.35 9519.35 9549.36 9569.36 9589.36 9599.36 9629.36 9649.37 9659.37
 9669.37 9679.37 9699.37 9719.38 9729.38 9749.38 9759.38 9769.38 9779.38 9789.38
 9799.38 9809.39 9819.39 9839.39 9849.39 9869.39 9879.39 9899.40 9909.40 9919.40
 9939.32 9942.93 9942.9310026.2610026.2610049.5710059.5910119.6810129.6910134.02
   54.39   53.99   53.60   52.17   50.79   49.25   48.39   46.33   46.07   45.85
   45.44   45.13   44.03   42.79   42.27   41.03   40.21   39.69   39.21   39.14
   38.93   38.55   37.91   36.18   35.13   33.47   32.73   32.31   32.70   33.44
   35.29   35.24   35.24   34.17   34.17   33.82   33.07   27.92   27.55   27.47
 -945.61 -946.01 -946.40 -947.83 -949.21 -950.75 -951.61 -953.67 -953.93 -954.15
 -954.56 -954.87 -955.97 -957.21 -957.73 -958.97 -959.79 -960.31 -960.79 -960.86
 -961.07 -961.45 -962.09 -963.82 -964.87 -966.53 -967.27 -967.69 -967.30 -966.56
 -964.71 -964.76   30.24   29.17 -965.83 -966.18 -966.93 -972.08 -972.45 -972.53
 9491.17 9499.35 9519.35 9549.36 9569.36 9589.36 9599.36 9629.36 9649.37 9659.37
 9669.37 9679.37 9699.37 9719.38 9729.38 9749.38 9759.38 9769.38 9779.38 9789.38
 9799.38 9809.39 9819.39 9839.39 9849.39 9869.39 9879.39 9899.40 9909.40 9919.40
 9938.39 9938.39 9939.3210021.7210021.7210049.5710059.5910119.6810129.6910134.02
   54.39   53.99   53.60   52.17   50.79   49.25   48.39   46.33   46.07   45.85
   45.44   45.13   44.03   42.79   42.27   41.03   40.21   39.69   39.21   39.14
   38.93   38.55   37.91   36.18   35.13   33.47   32.73   32.31   32.70   33.44
   35.20   35.20   35.29   34.23   34.23   33.82   33.07   27.92   27.55   27.47
 -945.61 -946.01 -946.40 -947.83 -949.21 -950.75 -951.61 -953.67 -953.93 -954.15
 -954.56 -954.87 -955.97 -957.21 -957.73 -958.97 -959.79 -960.31 -960.79 -960.86
 -961.07 -961.45 -962.09 -963.82 -964.87 -966.53 -967.27 -967.69 -967.30 -966.56
 -964.80   30.20   30.29   29.23 -965.77 -966.18 -966.93 -972.08 -972.45 -972.53
BR Coef=-1 , 0 , 0 ,, 0 ,,,0.8,0,1,0,
WSPro=,,,, 1 ,,,, 0 ,,,, 0 ,,,,-1 ,-1 ,-1 , 0 , 0 , 0 , 0 , 0
BC Design=,, 0 ,, 0 ,,,,,,

Type RM Length L Ch R = 1 ,7345.291,909.448500,909.448500,909.448500
XS GIS Cut Line= 3
411779.632207096790178.433240697411828.968162209 791865.92143257
412180.095170081792710.117268488
#Sta/Elev= 30
9447.28757.705499483.86954.879879523.88654.539759613.92546.526439653.94246.42933
9703.96338.646219804.00637.985499864.03229.355419904.049 29.06629914.05333.56793
9924.05733.666499934.06132.454599944.06616.070629964.07416.5635710004.0913.45412
 10024.127.8192710054.1130.1523310094.1327.3419710194.1725.41005 10734.427.12787
11229.3223.1713811489.7125.5244811698.0332.8029411795.1638.8066111849.3139.70764
11935.9646.3198811984.4653.3877212000.94 52.660612011.7754.71715 12049.855.84127
#Mann= 3 , 0 , 0
9447.287  0.0574       09447.287  0.0574       0 12049.8  0.0574       0
#XS Ineff= 2 , 0
       09914.427                       0
Bank Sta=9447.287,12049.8
Exp/Cntr=0.3,0.1

Type RM Length L Ch R = 1 ,6435.842,776.110000,776.110000,776.110000
XS GIS Cut Line= 4
411240.093017429 790375.49942407411385.102005243 791481.19295609
 411645.51867187791589.699900523411675.323265314792620.938832894
#Sta/Elev= 30
8733.41962.231928843.85759.876858853.94357.952768864.02852.86765  8884.249.36967
8924.54248.77223 8974.9744.357939085.91245.185519166.59736.24973 9206.9436.55271
9287.625 29.01479418.73822.041359842.33523.86234 9945.9722.575829967.63713.65767
10000.1411.7722110032.6412.9354910043.47  22.16210065.1422.3663810097.6426.23551
10316.0826.5218710356.0929.3224910446.13 25.907410626.2126.7929910816.2822.99233
10866.3124.2668410886.3121.8008210996.3624.2369211076.3932.7109611162.3734.51192
#Mann= 3 , 0 , 0
8733.419  0.0595       08733.419  0.0595       011162.37  0.0595       0
#XS Ineff= 2 , 0
       09819.907                       0
Bank Sta=8733.419,11162.37
Exp/Cntr=0.3,0.1

Type RM Length L Ch R = 1 ,5659.732,273.809500,273.809500,273.809500
XS GIS Cut Line= 3
410872.931537896790437.863702953411067.645693898791784.484968707
411137.090138346792909.484968707
#Sta/Elev= 30
8424.25959.964448492.09359.533478522.405 52.79758578.46951.485828613.34147.39906
8724.48546.484878865.94140.736099068.02140.424779158.95725.441569411.557 23.5864
9633.84526.846299684.36518.774319925.66718.426989945.70510.2340110005.829.817833
10015.8411.5311910025.8619.9189110055.9123.4868810126.05 25.550110256.2922.31197
10286.3518.1901510306.3920.8200910586.9222.3854810667.08 17.830110727.19 23.2233
10737.2125.2674910777.2843.8687210797.3248.8440210877.47 65.893710912.0367.37847
#Mann= 3 , 0 , 0
8424.259  0.0912       08424.259  0.0912       010912.03  0.0912       0
#XS Ineff= 2 , 0
       0 9774.36                       0
Bank Sta=8424.259,10912.03
Exp/Cntr=0.3,0.1

Type RM Length L Ch R = 3 ,5506.773,,,
BEGIN DESCRIPTION:
END DESCRIPTION:
Bridge Culvert--1,0,-1,-1, 0
Deck Dist Width WeirC Skew NumUp NumDn MinLoCord MaxHiCord MaxSubmerge Is_Ogee
92.941600,87.926300,2.6,0, 56, 56, , , 0.95, 0, 0,0,,
 9832.90 9841.61 9851.70 9859.86 9860.42 9861.78 9866.53 9871.78 9881.78 9891.78
 9901.78 9911.78 9921.78 9931.78 9934.92 9941.32 9941.3210022.3610022.3610067.72
10071.7910081.7910091.7910101.7910111.8010121.8010123.0310131.8510141.9210151.05
10151.9810162.0510172.1110182.1810192.2410202.3110212.3710222.4410232.5010239.16
10242.5710252.6310262.7010272.7610282.8310292.8910302.9610313.0210323.0910327.28
10333.1510343.2210353.2810363.3510373.4110377.25
   29.40   29.67   29.65   29.70   29.70   29.71   29.94   30.19   30.04   30.03
   30.17   30.11   30.11   30.22   30.32   30.30   30.30   30.08   30.08   29.95
   29.88   29.69   29.49   29.23   28.92   28.64   28.60   28.31   27.82   27.43
   27.40   27.00   26.69   26.34   26.04   25.65   25.27   24.89   24.55   24.34
   24.23   23.88   23.57   23.22   22.88   22.62   22.29   22.17   22.13   22.28
   22.47   21.65   20.88   20.01   19.42   19.18
 -970.60 -970.33 -970.35 -970.30 -970.30 -970.29 -970.06 -969.81 -969.96 -969.97
 -969.83 -969.89 -969.89 -969.78 -969.68 -969.70   25.30   25.08 -969.92 -970.05
 -970.12 -970.31 -970.51 -970.77 -971.08 -971.36 -971.40 -971.69 -972.18 -972.57
 -972.60 -973.00 -973.31 -973.66 -973.96 -974.35 -974.73 -975.11 -975.45 -975.66
 -975.77 -976.12 -976.43 -976.78 -977.12 -977.38 -977.71 -977.83 -977.87 -977.72
 -977.53 -978.35 -979.12 -979.99 -980.58 -980.82
 9832.90 9841.61 9851.70 9859.86 9860.42 9861.78 9866.53 9871.78 9881.78 9891.78
 9901.78 9911.78 9921.78 9931.78 9934.92 9963.73 9963.7310044.7710044.7710067.72
10071.7910081.7910091.7910101.7910111.8010121.8010123.0310131.8510141.9210151.05
10151.9810162.0510172.1110182.1810192.2410202.3110212.3710222.4410232.5010239.16
10242.5710252.6310262.7010272.7610282.8310292.8910302.9610313.0210323.0910327.28
10333.1510343.2210353.2810363.3510373.4110377.25
   29.40   29.67   29.65   29.70   29.70   29.71   29.94   30.19   30.04   30.03
   30.17   30.11   30.11   30.22   30.32   30.24   30.24   30.01   30.01   29.95
   29.88   29.69   29.49   29.23   28.92   28.64   28.60   28.31   27.82   27.43
   27.40   27.00   26.69   26.34   26.04   25.65   25.27   24.89   24.55   24.34
   24.23   23.88   23.57   23.22   22.88   22.62   22.29   22.17   22.13   22.28
   22.47   21.65   20.88   20.01   19.42   19.18
 -970.60 -970.33 -970.35 -970.30 -970.30 -970.29 -970.06 -969.81 -969.96 -969.97
 -969.83 -969.89 -969.89 -969.78 -969.68 -969.76   25.24   25.01 -969.99 -970.05
 -970.12 -970.31 -970.51 -970.77 -971.08 -971.36 -971.40 -971.69 -972.18 -972.57
 -972.60 -973.00 -973.31 -973.66 -973.96 -974.35 -974.73 -975.11 -975.45 -975.66
 -975.77 -976.12 -976.43 -976.78 -977.12 -977.38 -977.71 -977.83 -977.87 -977.72
 -977.53 -978.35 -979.12 -979.99 -980.58 -980.82
BR Coef=-1 , 0 , 0 ,, 0 ,,,0.8,0,1,0,
WSPro=,,,, 1 ,,,, 0 ,,,, 0 ,,,,-1 ,-1 ,-1 , 0 , 0 , 0 , 0 , 0
BC Design=,, 0 ,, 0 ,,,,,,

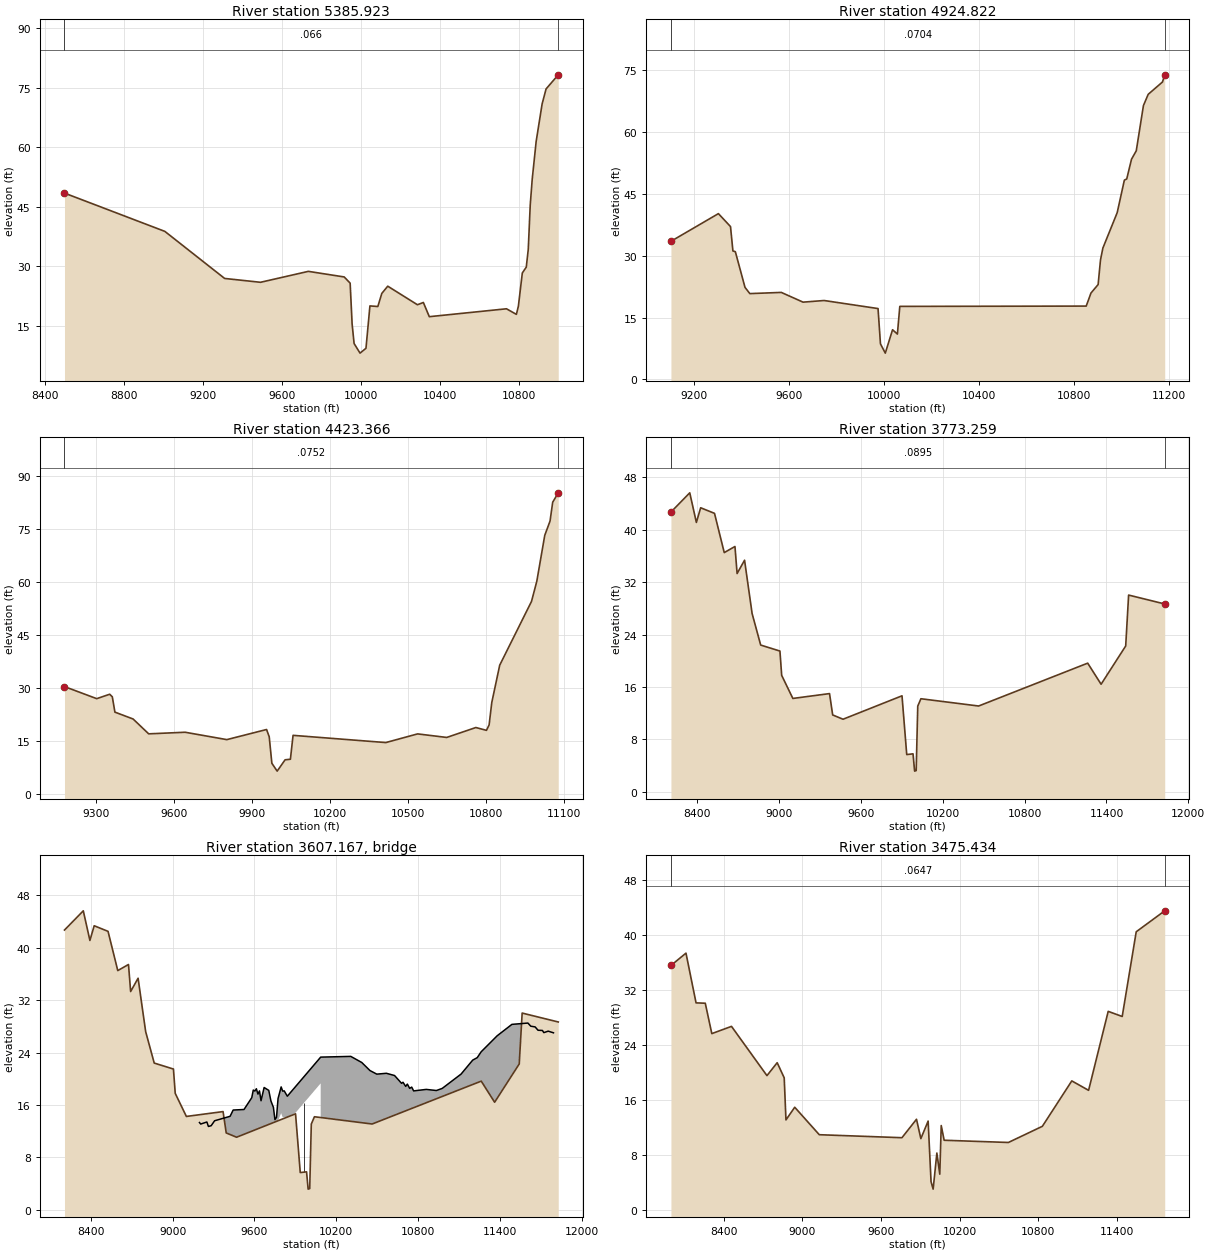
Type RM Length L Ch R = 1 ,5385.923,461.100700,461.100700,461.100700
XS GIS Cut Line= 3
410617.025087774790461.366097525410815.489970893791850.010262758
410901.637699813 792946.56345509
#Sta/Elev= 30
8496.73148.424819005.48338.760459308.53126.88055 9490.3625.912129732.799 28.6696
9914.52227.260089944.614 25.69739954.64515.398729964.67610.455489994.7688.035164
10024.869.25660910044.9219.9460210085.0519.8037910105.1123.10402 10135.224.93042
10285.6620.2458110315.7520.8143110345.8517.2333110737.0519.22467 10787.2 17.8192
10797.2319.84702 10817.328.2570410837.3629.7454610847.3934.1965510857.42 45.4168
10867.4551.9196510887.5161.48845 10917.670.9093610937.6674.7074910999.4278.27155
#Mann= 3 , 0 , 0
8496.731   0.066       08496.731   0.066       010999.42   0.066       0
#XS Ineff= 2 , 0
       09817.323                       0
Bank Sta=8496.731,10999.42
Exp/Cntr=0.3,0.1

Type RM Length L Ch R = 1 ,4924.822,501.455800,501.455800,501.455800
XS GIS Cut Line= 3
 410200.80191195791018.747187451410410.871356398792089.927743018
410317.121356398793074.302743003
#Sta/Elev= 30
9101.54533.485819301.536 40.19469352.488 37.05529362.67931.146349372.869 30.9672
9413.63122.309489434.01220.804389566.488 21.09429658.20318.734279746.916 19.1315
9974.10817.176329984.2988.62116710004.686.37482610035.2512.0455710055.6310.99574
10065.8217.7055710851.1717.7789310871.2620.9416310901.3922.9995510911.4429.00438
10921.4831.8558610981.7540.4307411011.8948.3036411021.9448.6065111042.0353.38011
11062.1255.4352211092.2566.3887711112.3469.1149611172.6172.1153311181.9673.84584
#Mann= 3 , 0 , 0
9101.545  0.0704       09101.545  0.0704       011181.96  0.0704       0
#XS Ineff= 2 , 0
       09682.727                       0
Bank Sta=9101.545,11181.96
Exp/Cntr=0.3,0.1

Type RM Length L Ch R = 1 ,4423.366,650.107700,650.107700,650.107700
XS GIS Cut Line= 3
409879.621356398791240.969409674409863.996356398791834.719409689
410119.204689741793115.969409689
#Sta/Elev= 30
9178.51830.388939302.59226.964429352.60928.216339362.61227.486679372.61623.14212
 9442.6421.192099502.66116.978589642.70917.434549803.349 15.34089956.296 18.2104
9966.492 16.16029976.6898.6258359997.0826.40285810027.679.61831510048.069.774514
10058.26 16.553810415.1414.5053310537.4916.9643610649.6515.9615310761.8218.77355
 10802.617.97148 10812.819.5181910822.9925.8423910853.5836.4585410975.9454.55244
10996.3360.2649611026.9273.2871111047.3277.3651811057.5182.7006111078.8985.36309
#Mann= 3 , 0 , 0
9178.518  0.0752       09178.518  0.0752       011078.89  0.0752       0
#XS Ineff= 2 , 0
       09440.976                       0
Bank Sta=9178.518,11078.89
Exp/Cntr=0.3,0.1

Type RM Length L Ch R = 1 ,3773.259,297.824400,297.824400,297.824400
XS GIS Cut Line= 6
409601.409550846790776.386076331 408868.77066198791380.552743018
409406.965106398792342.358298555 409431.27066195792620.136076346
409382.659550875792831.941631913408997.242884159793831.941631913
#Sta/Elev= 30
8207.02142.712118344.94545.648278393.45641.127218424.89243.367328526.408 42.5134
8597.78836.521518676.37837.452918692.09533.324648746.75635.35669 8802.1227.21313
8864.99222.399629005.98821.48782 9018.9517.774579100.75914.248829369.70614.98988
9392.80911.73145 9468.7311.074189901.078 14.65179935.7325.6796589981.9395.790817
 9993.493.15024510005.043.22924810016.5913.08104 10039.714.2037810462.76  13.093
11262.4819.6388611360.7316.4175411541.1222.2615911562.5530.03517 11827.228.67527
#Mann= 3 , 0 , 0
8207.021  0.0895       08207.021  0.0895       0 11827.2  0.0895       0
#XS Ineff= 2 , 0
       09128.503        10116.91       0
Bank Sta=8207.021,11827.2
Exp/Cntr=0.3,0.1

Type RM Length L Ch R = 3 ,3607.167,,,
BEGIN DESCRIPTION:
END DESCRIPTION:
Bridge Culvert--1,0,-1,-1, 0
Deck Dist Width WeirC Skew NumUp NumDn MinLoCord MaxHiCord MaxSubmerge Is_Ogee
76.412200,145.000000,2.6,0, 60, 60, , , 0.95, 0, 0,0,,
 9196.78 9205.78 9250.93 9262.28 9282.76 9307.66 9421.11 9443.80 9523.22 9579.95
 9591.29 9602.64 9613.98 9625.33 9636.67 9648.02 9670.71 9704.75 9720.47 9720.47
 9738.78 9750.13 9761.47 9772.82 9795.51 9806.86 9818.20 9840.8910085.4710085.47
10306.0510386.5410446.6610496.7610566.9010627.0210678.2210688.8710708.6410720.81
10737.7810752.7510766.9210859.2110933.7410976.3211114.7311199.9011233.1511262.29
11378.8411487.3611604.4711625.7611657.7011679.0011710.9411721.5811753.5211792.17
   13.32   13.09   13.40   12.72   12.84   13.59   14.27   15.23   15.31   17.11
   18.28   18.13   18.48   17.66   18.15   16.65   18.67   18.23   16.63   16.63
   15.64   13.77   14.12   16.98   18.76   18.12   18.15   17.34   23.31   23.31
   23.42   22.49   21.26   20.71   20.84   20.50   19.31   19.47   18.84   19.19
   18.54   18.73   18.15   18.38   18.21   18.53   20.72   22.85   23.23   24.13
   26.56   28.31   28.51   28.03   27.92   27.41   27.38   27.05   27.27   27.02
 -986.68 -986.91 -986.60 -987.28 -987.16 -986.41 -985.73 -984.77 -984.69 -982.89
 -981.72 -981.87 -981.52 -982.34 -981.85 -983.35 -981.33 -981.77 -983.37   12.63
   11.64    9.77   10.12   12.98   14.76   14.12   14.15   13.34   19.31 -976.69
 -976.58 -977.51 -978.74 -979.29 -979.16 -979.50 -980.69 -980.53 -981.16 -980.81
 -981.46 -981.27 -981.85 -981.62 -981.79 -981.47 -979.28 -977.15 -976.77 -975.87
 -973.44 -971.69 -971.49 -971.97 -972.08 -972.59 -972.62 -972.95 -972.73 -972.98
 9196.78 9205.78 9250.93 9262.28 9282.76 9307.66 9421.11 9443.80 9523.22 9579.95
 9591.29 9602.64 9613.98 9625.33 9636.67 9648.02 9670.71 9704.75 9716.09 9738.78
 9750.13 9761.47 9772.82 9795.51 9798.30 9798.30 9806.86 9818.20 9840.8910089.30
10163.3010163.3010308.7910386.5410496.7610566.9010627.0210678.2210688.8710708.64
10720.8110737.7810752.7510766.9210933.7410976.3211114.7311199.9011233.1511262.29
11378.8411487.3611604.4711625.7611657.7011679.0011710.9411721.5811753.5211792.17
   13.32   13.09   13.40   12.72   12.84   13.59   14.27   15.23   15.31   17.11
   18.28   18.13   18.48   17.66   18.15   16.65   18.67   18.23   16.91   15.64
   13.77   14.12   16.98   18.76   18.60   18.60   18.12   18.15   17.34   23.41
   23.41   23.41   23.40   22.49   20.71   20.84   20.50   19.31   19.47   18.84
   19.19   18.54   18.73   18.15   18.21   18.53   20.72   22.85   23.23   24.13
   26.56   28.31   28.51   28.03   27.92   27.41   27.38   27.05   27.27   27.02
 -986.68 -986.91 -986.60 -987.28 -987.16 -986.41 -985.73 -984.77 -984.69 -982.89
 -981.72 -981.87 -981.52 -982.34 -981.85 -983.35 -981.33 -981.77 -983.09 -984.36
 -986.23 -985.88 -983.02 -981.24 -981.40   14.60   14.12   14.15   13.34   19.41
   19.41 -976.59 -976.60 -977.51 -979.29 -979.16 -979.50 -980.69 -980.53 -981.16
 -980.81 -981.46 -981.27 -981.85 -981.79 -981.47 -979.28 -977.15 -976.77 -975.87
 -973.44 -971.69 -971.49 -971.97 -972.08 -972.59 -972.62 -972.95 -972.73 -972.98
Pier Skew, UpSta & Num, DnSta & Num=  ,9841.63, 2 ,9919.47, 2 , 0 , 0 , 0 ,,
    3.00    3.00
 -982.64   17.36
    3.00    3.00
 -980.74   19.26
Pier Skew, UpSta & Num, DnSta & Num=  ,9964.30, 2 ,10042.14, 2 , 0 , 0 , 0 ,,
    3.00    3.00
 -979.64   20.36
    3.00    3.00
 -977.74   22.26
BR Coef=-1 , 0 , 0 ,, 0 ,,,0.8,0,1,0,
WSPro=,,,, 1 ,,,, 0 ,,,, 0 ,,,,-1 ,-1 ,-1 , 0 , 0 , 0 , 0 , 0
BC Design=,, 0 ,, 0 ,,,,,,

Type RM Length L Ch R = 1 ,3475.434,640.489500,640.489500,640.489500
XS GIS Cut Line= 6
409500.715106398790637.497187451408643.076217502791401.386076346
409070.159550846792283.330520779409198.631773055792599.302743003
409163.909550875792838.886076331408788.909550846793828.469409674
#Sta/Elev= 30
7996.74635.602858111.53237.401138188.44730.155538258.83830.105118308.727 25.6774
8459.07726.732818729.70719.55726 8807.8921.441098861.45619.237268874.84813.10786
8941.80514.950789129.28710.950489760.36410.514269871.47213.199929904.80410.38222
9960.35812.93692 9982.584.1093499998.6063.02366310027.028.27945710049.245.202616
10060.3612.2837110082.5810.1440710573.06 9.8203910832.5212.1748711057.0918.79009
11185.4117.4158311335.13 28.917811442.0728.1729911549.0140.51241 11766.643.56459
#Mann= 3 , 0 , 0
7996.746  0.0647       07996.746  0.0647       0 11766.6  0.0647       0
#XS Ineff= 2 , 0
       09081.741        10207.77       0
Bank Sta=7996.746,11766.6
Exp/Cntr=0.3,0.1

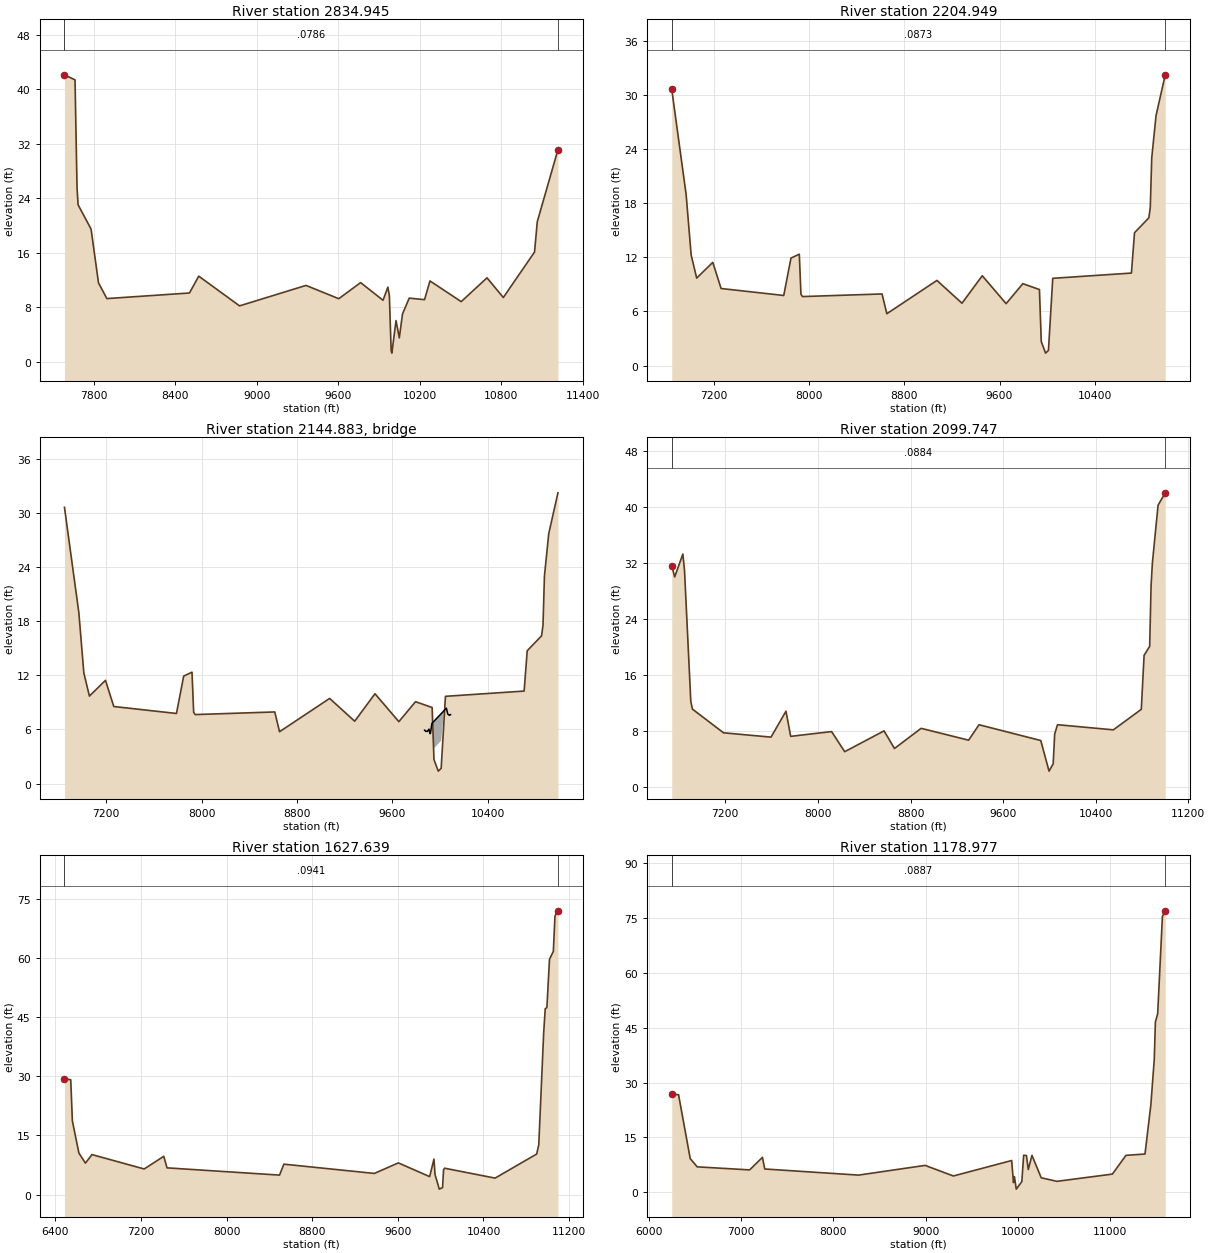
Type RM Length L Ch R = 1 ,2834.945,629.996000,629.996000,629.996000
XS GIS Cut Line= 5
409298.053069353790231.590792775 408402.21973601791192.528292775
408305.865569353 792067.52829279 408542.84473601792429.507459447
408516.803069353793437.319959447
#Sta/Elev= 30
7583.68842.15289 7661.4941.412517676.15525.639297684.04923.063237779.74919.48495
7834.43511.58609 7896.139.2805728504.33610.100858572.69412.574828873.4668.208833
9362.69711.214059604.1489.2622749765.11511.626949930.0789.0350089965.93610.96149
9976.9659.679177 9989.841.6475699995.222 1.26661 10025.76.04722710049.993.509176
10073.517.01606410123.029.34871810235.879.12236110275.89 11.872510505.968.831287
10696.0312.3289610816.079.43535211046.1416.1183811066.1520.5645411218.5231.15328
#Mann= 3 , 0 , 0
7583.688  0.0786       07583.688  0.0786       011218.52  0.0786       0
#XS Ineff= 2 , 0
       08991.928        10518.65       0
Bank Sta=7583.688,11218.52
Exp/Cntr=0.3,0.1

Type RM Length L Ch R = 1 ,2204.949,105.201800,105.201800,105.201800
XS GIS Cut Line= 4
409071.490569353789918.873778895407864.893347144791095.089056656
407795.448902696792423.214056671408423.053069353793359.194959447
#Sta/Elev= 30
6848.83730.623736969.62318.943427011.518 12.26637058.1769.7036317193.06611.44603
7262.892 8.54674  7788.87.7754157849.43211.917377919.258 12.35227933.2237.904857
7946.3857.6529858613.8977.9441688653.951 5.752219074.5259.4429259284.812 6.91681
9455.0449.9607879655.3176.8682289795.5099.0827389934.833 8.433079950.2462.659187
9986.3661.38605810010.451.68941610046.579.67610710706.94 10.258110732.84 14.7286
10853.2416.3792510865.2817.5498910877.3223.0029610913.4427.7071610990.7432.22751
#Mann= 3 , 0 , 0
6848.837  0.0873       06848.837  0.0873       010990.74  0.0873       0
#XS Ineff= 2 , 0
       08537.687        10545.66       0
Bank Sta=6848.837,10990.74
Exp/Cntr=0.3,0.1

Type RM Length L Ch R = 3 ,2144.883,,,
BEGIN DESCRIPTION:
END DESCRIPTION:
Bridge Culvert--1,0,-1,-1, 0
Deck Dist Width WeirC Skew NumUp NumDn MinLoCord MaxHiCord MaxSubmerge Is_Ogee
49.100900,7.000000,2.6,0, 21, 21, , , 0.95, 0, 0,0,,
 9871.48 9872.03 9881.39 9884.16 9896.29 9899.05 9908.42 9916.72 9920.55 9926.59
 9926.59 9932.5910051.5910051.5910053.8310053.9910058.0310066.1310075.6910078.26
10089.16
    5.93    5.93    5.79    5.80    5.79    5.86    6.04    5.54    5.56    6.11
    6.11    6.67    8.32    8.32    8.35    8.37    8.15    7.70    7.62    7.57
    7.64
 -994.07 -994.07 -994.21 -994.20 -994.21 -994.14 -993.96 -994.46 -994.44 -993.89
    3.11    3.67    5.32 -991.68 -991.65 -991.63 -991.85 -992.30 -992.38 -992.43
 -992.36
 9871.48 9872.03 9881.39 9884.16 9896.29 9899.05 9908.42 9916.72 9920.55 9932.54
 9932.54 9932.5910053.8310053.9910057.5410057.5410058.0310066.1310075.6910078.26
10089.16
    5.93    5.93    5.79    5.80    5.79    5.86    6.04    5.54    5.56    6.66
    6.66    6.67    8.35    8.37    8.18    8.18    8.15    7.70    7.62    7.57
    7.64
 -994.07 -994.07 -994.21 -994.20 -994.21 -994.14 -993.96 -994.46 -994.44 -993.34
    3.66    3.67    5.35    5.37    5.18 -991.82 -991.85 -992.30 -992.38 -992.43
 -992.36
BR Coef=-1 , 0 , 0 ,, 0 ,,,0.8,0,1,0,
WSPro=,,,, 1 ,,,, 0 ,,,, 0 ,,,,-1 ,-1 ,-1 , 0 , 0 , 0 , 0 , 0
BC Design=,, 0 ,, 0 ,,,,,,

Type RM Length L Ch R = 1 ,2099.747,472.108500,472.108500,472.108500
XS GIS Cut Line= 4
 408953.00098601789858.688593701407751.385487378 791059.61542502
 407703.00098601792473.271927029408347.098208249793426.396927029
#Sta/Elev= 30
6737.18531.558066762.63529.956846833.32533.227026847.46330.873746901.72112.17022
6915.86711.072737184.6457.6862677594.8847.0703557724.02410.771417764.6397.180741
8118.2947.8606768231.4634.9881848571.5037.9614758661.5555.443853 8891.698.326595
 9301.936.6332549391.9838.8381629925.533 6.582879996.9732.21282510032.693.258617
10045.727.51254910069.868.84112910552.638.11117110794.0111.0395210818.1518.75038
10866.4320.04226 10878.528.7124310889.9731.9804910938.8440.1956111000.8741.96806
#Mann= 3 , 0 , 0
6737.185  0.0884       06737.185  0.0884       011000.87  0.0884       0
#XS Ineff= 2 , 0
       08434.959        10544.34       0
Bank Sta=6737.185,11000.87
Exp/Cntr=0.3,0.1

Type RM Length L Ch R = 1 ,1627.639,448.661500,448.661500,448.661500
XS GIS Cut Line= 6
408891.142431796789836.525147259407832.114654034 790756.66403614
407667.184098482 791051.80292502407380.725765139792531.837647244
407402.427154034 793256.66403614407823.434098482793734.094591707
#Sta/Elev= 30
6485.57829.33192 6544.2429.099966559.48718.656996620.47510.499016681.4627.968753
 6742.4510.130127230.3496.4808927413.3129.6919427443.8066.764925 8494.684.927997
8535.4227.7012799380.8255.3528239604.908 8.024099897.335 4.544299937.3538.972324
9947.3585.0867529987.3761.37472710017.39 1.7538910027.396.324452 10037.46.675682
 10508.54.16486310897.0110.2653910916.73 12.601210962.0940.8061910977.0147.12568
10992.3247.36803   1101759.64302 11052.861.6451111067.9270.5862511095.7971.91306
#Mann= 3 , 0 , 0
6485.578  0.0941       06485.578  0.0941       011095.79  0.0941       0
#XS Ineff= 2 , 0
       08204.448         10524.5       0
Bank Sta=6485.578,11095.79
Exp/Cntr=0.3,0.1

Type RM Length L Ch R = 1 ,1178.977,237.887100,237.887100,237.887100
XS GIS Cut Line= 5
408903.492884189789713.886076331407809.742884189790555.899965242
406941.687328607792529.858298555407004.187328607793824.997187465
407302.798439771794241.663854122
#Sta/Elev= 30
6248.054 26.89436321.87226.668546448.073  9.22636523.7936.9697247091.6956.135555
7230.5159.5665227255.7566.3834358271.9174.7094638992.9147.3668369298.7924.470515
9930.0758.6960669950.0992.659461 9960.114.3115149980.1330.878281 10040.22.911447
10060.2310.1419910090.2610.0600510110.286.23624810150.3310.1056710250.453.980162
10420.653.00774411021.344.98337711168.6410.1162311374.6410.46824 11438.2 23.9086
11475.1136.3648911487.4146.5662711512.0248.8165811563.4875.4335211594.0376.95512
#Mann= 3 , 0 , 0
6248.054  0.0887       06248.054  0.0887       011594.03  0.0887       0
#XS Ineff= 2 , 0
       08122.829        10652.85       0
Bank Sta=6248.054,11594.03
Exp/Cntr=0.3,0.1