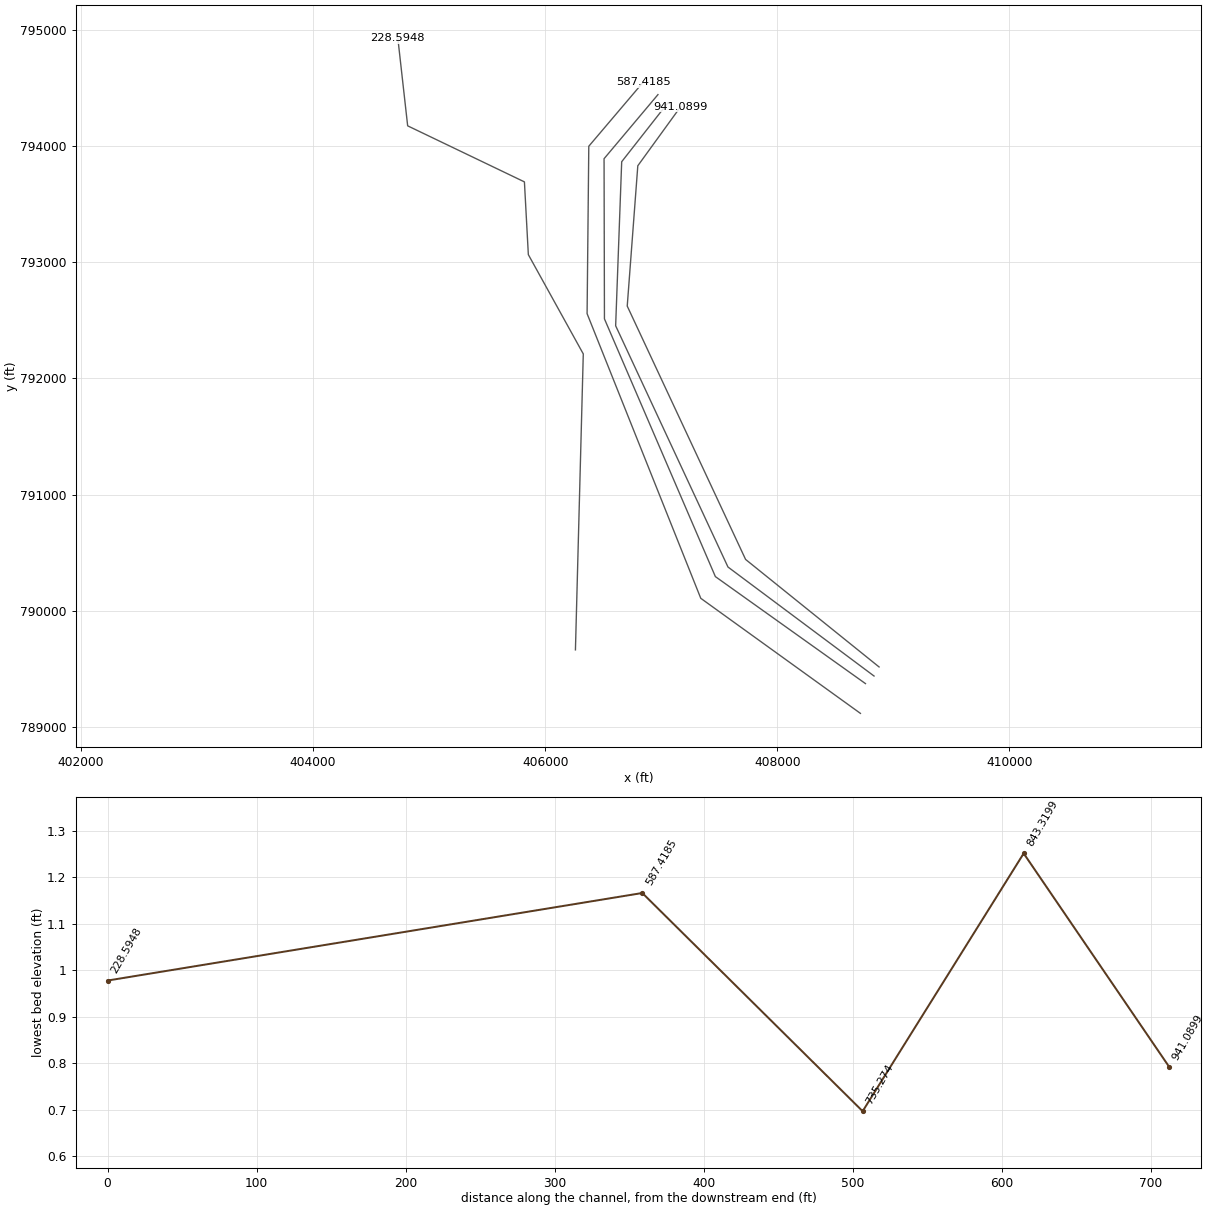
HEC-RAS study 4217_ras.prj: 4217

--- 4217_ras.g01 (geometry) --- (continued)

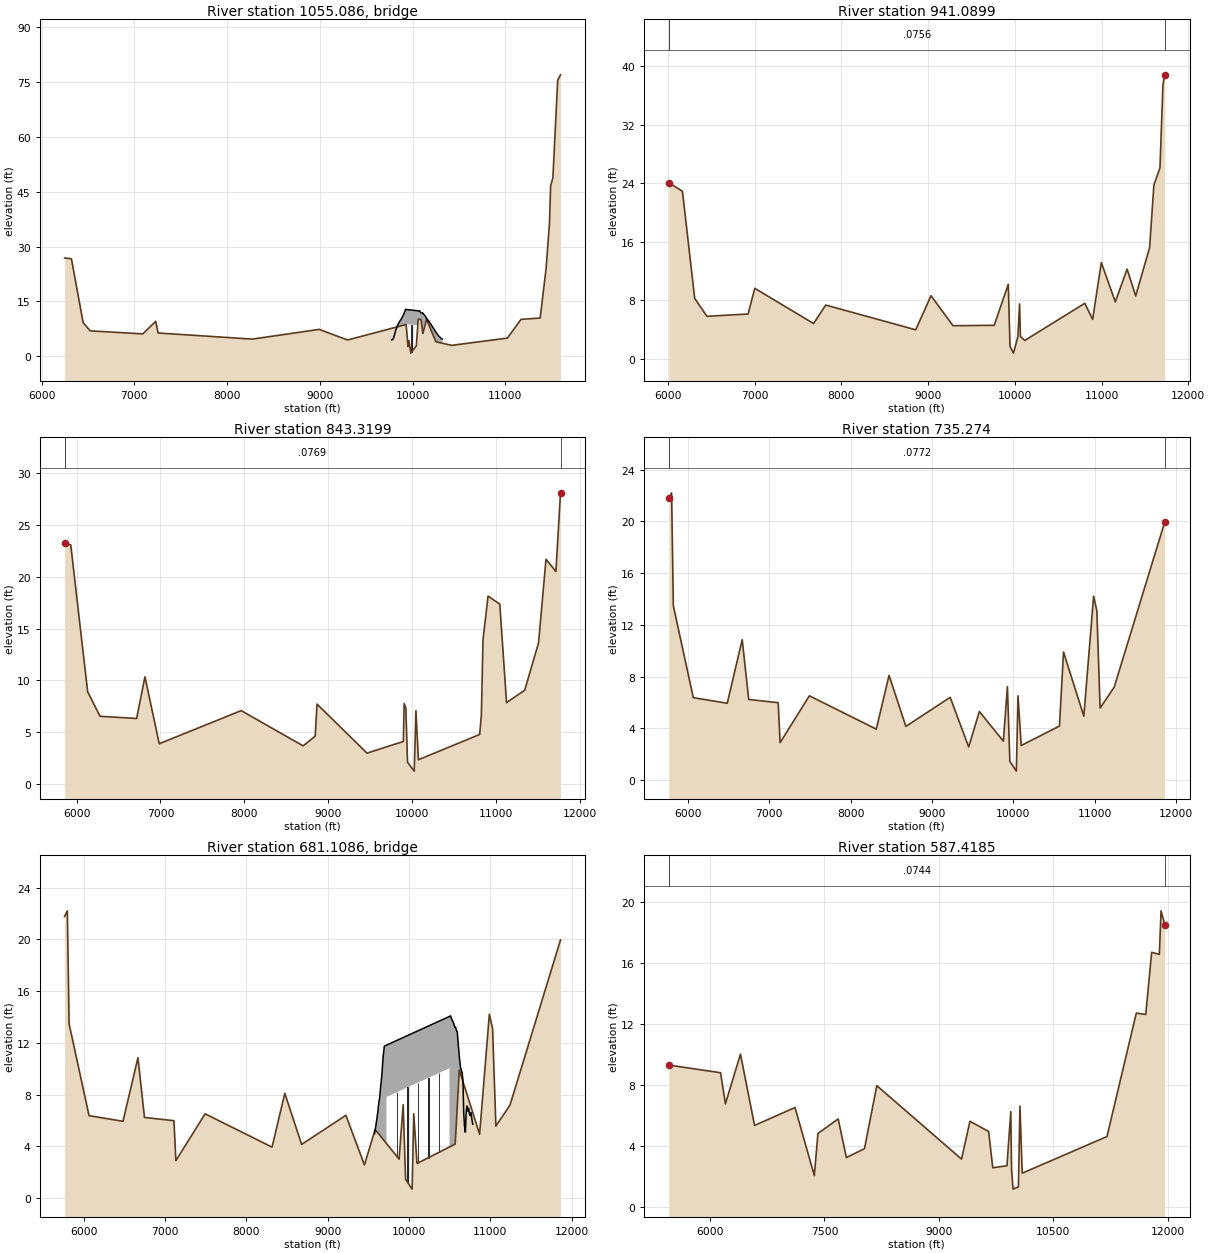
Type RM Length L Ch R = 3 ,1055.086,,,
BEGIN DESCRIPTION:
END DESCRIPTION:
Bridge Culvert--1,0,-1,-1, 0
Deck Dist Width WeirC Skew NumUp NumDn MinLoCord MaxHiCord MaxSubmerge Is_Ogee
66.778300,104.330500,2.6,0, 52, 52, , , 0.95, 0, 0,0,,
 9776.11 9782.99 9788.64 9793.99 9804.98 9812.69 9815.98 9824.83 9826.78 9836.78
 9846.78 9856.78 9866.78 9876.78 9886.78 9896.78 9906.78 9916.78 9921.19 9921.19
 9924.9210052.4310052.4310075.3910076.7810086.7810096.7810106.7810116.7810126.78
10127.7810136.8110146.8410156.8710166.9010176.9310186.9610196.9910203.9310207.02
10217.0510227.0810237.1110247.1410257.1710267.2010277.2310287.2610297.2910307.32
10317.3510319.70
    4.51    4.56    4.75    5.00    5.95    6.65    6.97    7.66    7.77    8.40
    8.97    9.41    9.79   10.15   10.68   11.13   11.67   12.39   12.63   12.63
   12.83   12.46   12.46   12.39   12.46   11.90   11.75   11.91   11.55   11.28
   11.25   10.98   10.53   10.14    9.86    9.52    9.15    8.79    8.47    8.33
    7.90    7.54    7.16    6.76    6.36    6.00    5.69    5.42    5.16    4.89
    4.75    4.71
 -995.49 -995.44 -995.25 -995.00 -994.05 -993.35 -993.03 -992.34 -992.23 -991.60
 -991.03 -990.59 -990.21 -989.85 -989.32 -988.87 -988.33 -987.61 -987.37    8.63
    8.83    8.46 -987.54 -987.61 -987.54 -988.10 -988.25 -988.09 -988.45 -988.72
 -988.75 -989.02 -989.47 -989.86 -990.14 -990.48 -990.85 -991.21 -991.53 -991.67
 -992.10 -992.46 -992.84 -993.24 -993.64 -994.00 -994.31 -994.58 -994.84 -995.11
 -995.25 -995.29
 9776.11 9782.99 9788.64 9793.99 9804.98 9812.69 9815.98 9824.83 9826.78 9836.78
 9846.78 9856.78 9866.78 9876.78 9886.78 9896.78 9906.78 9916.78 9924.92 9933.62
 9933.6210064.8610064.8610075.3910076.7810086.7810096.7810106.7810116.7810126.78
10127.7810136.8110146.8410156.8710166.9010176.9310186.9610196.9910203.9310207.02
10217.0510227.0810237.1110247.1410257.1710267.2010277.2310287.2610297.2910307.32
10317.3510319.70
    4.51    4.56    4.75    5.00    5.95    6.65    6.97    7.66    7.77    8.40
    8.97    9.41    9.79   10.15   10.68   11.13   11.67   12.39   12.83   12.80
   12.80   12.42   12.42   12.39   12.46   11.90   11.75   11.91   11.55   11.28
   11.25   10.98   10.53   10.14    9.86    9.52    9.15    8.79    8.47    8.33
    7.90    7.54    7.16    6.76    6.36    6.00    5.69    5.42    5.16    4.89
    4.75    4.71
 -995.49 -995.44 -995.25 -995.00 -994.05 -993.35 -993.03 -992.34 -992.23 -991.60
 -991.03 -990.59 -990.21 -989.85 -989.32 -988.87 -988.33 -987.61 -987.17 -987.20
    8.80    8.42 -987.58 -987.61 -987.54 -988.10 -988.25 -988.09 -988.45 -988.72
 -988.75 -989.02 -989.47 -989.86 -990.14 -990.48 -990.85 -991.21 -991.53 -991.67
 -992.10 -992.46 -992.84 -993.24 -993.64 -994.00 -994.31 -994.58 -994.84 -995.11
 -995.25 -995.29
Pier Skew, UpSta & Num, DnSta & Num=  ,9986.81, 2 ,9999.24, 2 , 0 , 0 , 0 ,,
    4.00    4.00
 -987.35   12.65
    4.00    4.00
 -987.39   12.61
BR Coef=-1 , 0 , 0 ,, 0 ,,,0.8,0,1,0,
WSPro=,,,, 1 ,,,, 0 ,,,, 0 ,,,,-1 ,-1 ,-1 , 0 , 0 , 0 , 0 , 0
BC Design=,, 0 ,, 0 ,,,,,,

Type RM Length L Ch R = 1 ,941.0899,97.770000,97.770000,97.770000
XS GIS Cut Line= 5
408877.451217502789518.573576331407727.277606428790443.052743003
406707.312328637792621.872187465 406798.45816195793828.469409674
407167.381773084794336.281909689
#Sta/Elev= 30
6009.45924.084086166.56222.908766307.6918.2774666448.8195.8243456923.5246.134683
7000.5039.6467857679.1794.834464 7818.517.3615828856.409 3.977459033.0738.639006
9287.0274.5369689761.8114.5915889924.07710.197399944.1341.7186779984.2480.791422
10034.393.04630810054.457.51807910064.483.04400810114.622.52736910806.587.600065
10896.845.40481910997.1313.16336 11158.47.79551711294.3712.2746811393.258.615431
11553.9415.2063211603.3823.7525311673.4726.10806 11707.537.4381811728.57 38.8205
#Mann= 3 , 0 , 0
6009.459  0.0756       06009.459  0.0756       011728.57  0.0756       0
#XS Ineff= 2 , 0
       08059.596        10710.65       0
Bank Sta=6009.459,11728.57
Exp/Cntr=0.3,0.1

Type RM Length L Ch R = 1 ,843.3199,108.045900,108.045900,108.045900
XS GIS Cut Line= 5
408834.048439741789440.448576331407575.367884189790377.948576346
406607.485939741792452.601354137406659.569273055793863.191631913
407058.874828607794371.004131898
#Sta/Elev= 30
5855.97723.254835929.60423.074156131.4498.9041146278.7376.5426876715.1536.329441
6814.90610.351386985.2323.8948867962.877 7.087518702.2023.6860848845.4724.626434
8867.723 7.717449463.5972.9881629897.2714.1119379907.2787.7708649927.2927.338047
9947.3052.10316810027.361.25129210047.377.07869110077.392.35206410807.894.790788
 10827.96.62874210847.9213.9533910907.9618.1380211048.0517.35945 11128.67.858599
 11345.49.06296511510.2413.6234411599.2921.68874 11717.520.51251 11772.328.09981
#Mann= 3 , 0 , 0
5855.977  0.0769       05855.977  0.0769       0 11772.3  0.0769       0
#XS Ineff= 2 , 0
       08010.302        10726.73       0
Bank Sta=5855.977,11772.3
Exp/Cntr=0.3,0.1

Type RM Length L Ch R = 1 , 735.274,147.855500,147.855500,147.855500
XS GIS Cut Line= 5
408760.263717502789375.344409674407466.860939801790295.483298555
406510.943694353792511.813593701406507.659550846793889.233298555
406972.069273114794440.448576331
#Sta/Elev= 30
5763.75621.763425797.66322.199155819.30513.469696064.7526.3724596482.0115.940268
6666.09610.853216746.4546.2341287108.719 5.983987132.4452.8991057492.1136.515612
8315.2623.9412988472.2578.0972478679.176 4.15125  9223.7 6.399879451.5112.568089
9583.0855.302346 9877.943.014618 9927.947.222785 9957.941.44950610037.940.696686
10057.946.51918410097.942.67830410567.94 4.1773910617.949.89950510867.944.942594
10987.9414.2116511027.9413.0740811067.945.56943311241.257.18456111862.9519.94865
#Mann= 3 , 0 , 0
5763.756  0.0772       05763.756  0.0772       011862.95  0.0772       0
#XS Ineff= 2 , 0
       07975.973        10743.76       0
Bank Sta=5763.756,11862.95
Exp/Cntr=0.3,0.1

Type RM Length L Ch R = 3 ,681.1086,,,
BEGIN DESCRIPTION:
END DESCRIPTION:
Bridge Culvert--1,0,-1,-1, 0
Deck Dist Width WeirC Skew NumUp NumDn MinLoCord MaxHiCord MaxSubmerge Is_Ogee
48.927750,50.000000,2.6,0, 53, 53, , , 0.95, 0, 0,0,,
 9575.03 9583.30 9591.20 9594.15 9605.00 9615.84 9617.00 9626.69 9637.54 9642.80
 9648.39 9659.24 9668.60 9670.08 9680.93 9691.78 9694.40 9695.22 9722.40 9722.40
10497.4010497.4010511.4110512.8110522.8110532.8210542.8210552.8210562.8210572.82
10582.8210592.8210602.8310612.8310622.8310632.8310642.8310652.8310662.8310672.84
10680.4110682.8410692.8410702.8410712.8410722.8410732.8410742.8510752.8510762.85
10772.8510782.8510785.32
    4.97    5.31    5.55    5.70    6.15    6.66    6.72    7.30    7.71    8.04
    8.48    9.09    9.76    9.91   10.90   11.49   11.67   11.74   11.82   11.82
   14.04   14.04   14.08   14.05   13.85   13.73   13.60   13.44   13.20   13.20
   12.96   12.87   12.10   11.34   10.67   10.12    9.89    9.70    9.11    6.55
    5.78    5.55    5.09    6.63    7.12    6.73    6.95    6.52    6.38    6.60
    6.09    5.72    5.71
 -995.03 -994.69 -994.45 -994.30 -993.85 -993.34 -993.28 -992.70 -992.29 -991.96
 -991.52 -990.91 -990.24 -990.09 -989.10 -988.51 -988.33 -988.26 -988.18    7.82
   10.04 -985.96 -985.92 -985.95 -986.15 -986.27 -986.40 -986.56 -986.80 -986.80
 -987.04 -987.13 -987.90 -988.66 -989.33 -989.88 -990.11 -990.30 -990.89 -993.45
 -994.22 -994.45 -994.91 -993.37 -992.88 -993.27 -993.05 -993.48 -993.62 -993.40
 -993.91 -994.28 -994.29
 9575.03 9583.30 9591.20 9594.15 9605.00 9615.84 9617.00 9626.69 9637.54 9642.80
 9648.39 9659.24 9668.60 9670.08 9680.93 9691.78 9692.98 9692.98 9694.40 9695.22
10467.9810467.9810511.4110512.8110522.8110532.8210542.8210552.8210562.8210572.82
10582.8210592.8210602.8310612.8310622.8310632.8310642.8310652.8310662.8310672.84
10680.4110682.8410692.8410702.8410712.8410722.8410732.8410742.8510752.8510762.85
10772.8510782.8510785.32
    4.97    5.31    5.55    5.70    6.15    6.66    6.72    7.30    7.71    8.04
    8.48    9.09    9.76    9.91   10.90   11.49   11.57   11.57   11.67   11.74
   13.95   13.95   14.08   14.05   13.85   13.73   13.60   13.44   13.20   13.20
   12.96   12.87   12.10   11.34   10.67   10.12    9.89    9.70    9.11    6.55
    5.78    5.55    5.09    6.63    7.12    6.73    6.95    6.52    6.38    6.60
    6.09    5.72    5.71
 -995.03 -994.69 -994.45 -994.30 -993.85 -993.34 -993.28 -992.70 -992.29 -991.96
 -991.52 -990.91 -990.24 -990.09 -989.10 -988.51 -988.43    7.57    7.67    7.74
    9.95 -986.05 -985.92 -985.95 -986.15 -986.27 -986.40 -986.56 -986.80 -986.80
 -987.04 -987.13 -987.90 -988.66 -989.33 -989.88 -990.11 -990.30 -990.89 -993.45
 -994.22 -994.45 -994.91 -993.37 -992.88 -993.27 -993.05 -993.48 -993.62 -993.40
 -993.91 -994.28 -994.29
Pier Skew, UpSta & Num, DnSta & Num=  ,9850.24, 2 ,9820.81, 2 , 0 , 0 , 0 ,,
    4.00    4.00
 -987.82   12.18
    4.00    4.00
 -987.90   12.10
Pier Skew, UpSta & Num, DnSta & Num=  ,9980.07, 2 ,9950.65, 2 , 0 , 0 , 0 ,,
    4.00    4.00
 -987.44   12.56
    4.00    4.00
 -987.53   12.47
Pier Skew, UpSta & Num, DnSta & Num=  ,10109.90, 2 ,10080.48, 2 , 0 , 0 , 0 ,,
    4.00    4.00
 -987.07   12.93
    4.00    4.00
 -987.16   12.84
Pier Skew, UpSta & Num, DnSta & Num=  ,10239.74, 2 ,10210.31, 2 , 0 , 0 , 0 ,,
    4.00    4.00
 -986.70   13.30
    4.00    4.00
 -986.78   13.22
Pier Skew, UpSta & Num, DnSta & Num=  ,10369.57, 2 ,10340.15, 2 , 0 , 0 , 0 ,,
    4.00    4.00
 -986.33   13.67
    4.00    4.00
 -986.41   13.59
BR Coef=-1 , 0 , 0 ,, 0 ,,,0.8,0,1,0,
WSPro=,,,, 1 ,,,, 0 ,,,, 0 ,,,,-1 ,-1 ,-1 , 0 , 0 , 0 , 0 , 0
BC Design=,, 0 ,, 0 ,,,,,,

Type RM Length L Ch R = 1 ,587.4185,358.823700,358.823700,358.823700
XS GIS Cut Line= 5
408716.860939831789119.268020794407340.992884159790108.851354137
406361.392189771792556.768020824406375.994862378793996.290772244
406846.201217502794548.955520779
#Sta/Elev= 30
5461.6029.2923066139.3418.7923086202.9696.7595436400.05610.009626584.6235.341129
7114.4956.5116327367.6562.0562157414.7554.8124627680.0155.7663947787.7253.234677
8024.6863.8164688186.2517.9471999295.6633.1347359406.5055.6115429651.1064.944157
 9704.962.567963 9891.272.6986429941.2726.2457279951.2732.4589529971.274 1.16611
10041.28 1.3142810061.286.60151810091.28 2.2110611201.34 4.6114811585.4312.70011
11709.4912.6068711786.6516.6804111887.4116.5476411910.1119.3996411958.2618.49368
#Mann= 3 , 0 , 0
5461.602  0.0744       05461.602  0.0744       011958.26  0.0744       0
#XS Ineff= 2 , 0
       07914.174        10754.31       0
Bank Sta=5461.602,11958.26
Exp/Cntr=0.3,0.1

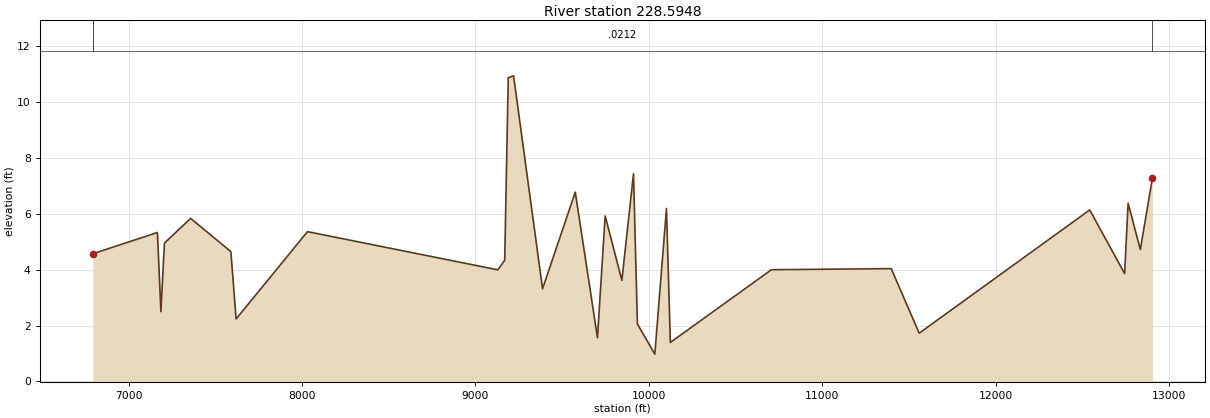
Type RM Length L Ch R = 1 ,228.5948,0.000000,0.000000,0.000000
XS GIS Cut Line= 6
406260.949533045789665.360402286406328.588823378792210.288700983
405855.113791078 793064.23474139405821.294145912793689.898176938
404815.159702301794171.828120574404730.610589325794924.315225467
#Sta/Elev= 30
6793.5094.5710077166.2275.3316267186.3932.499909 7206.56  4.95017357.8095.836844
7589.7244.6469237619.9732.2366938031.5085.362493 9128.753.9952799168.6084.336976
9189.032 10.87599219.66710.941179386.7963.316542 9575.366.7759799703.3811.564433
9747.7235.9236219844.0633.6173869911.1457.4314049933.5052.05912610034.130.977779
10101.216.19238310123.571.39515810706.453.99985411397.224.03819211558.171.727307
12541.456.13919812742.713.86256112762.846.37852712833.284.72138712903.037.281518
#Mann= 3 , 0 , 0
6793.509  0.0212       06793.509  0.0212       012903.03  0.0212       0
#XS Ineff= 2 , 0
       07705.598        10897.73       0
Bank Sta=6793.509,12903.03
Exp/Cntr=0.3,0.1